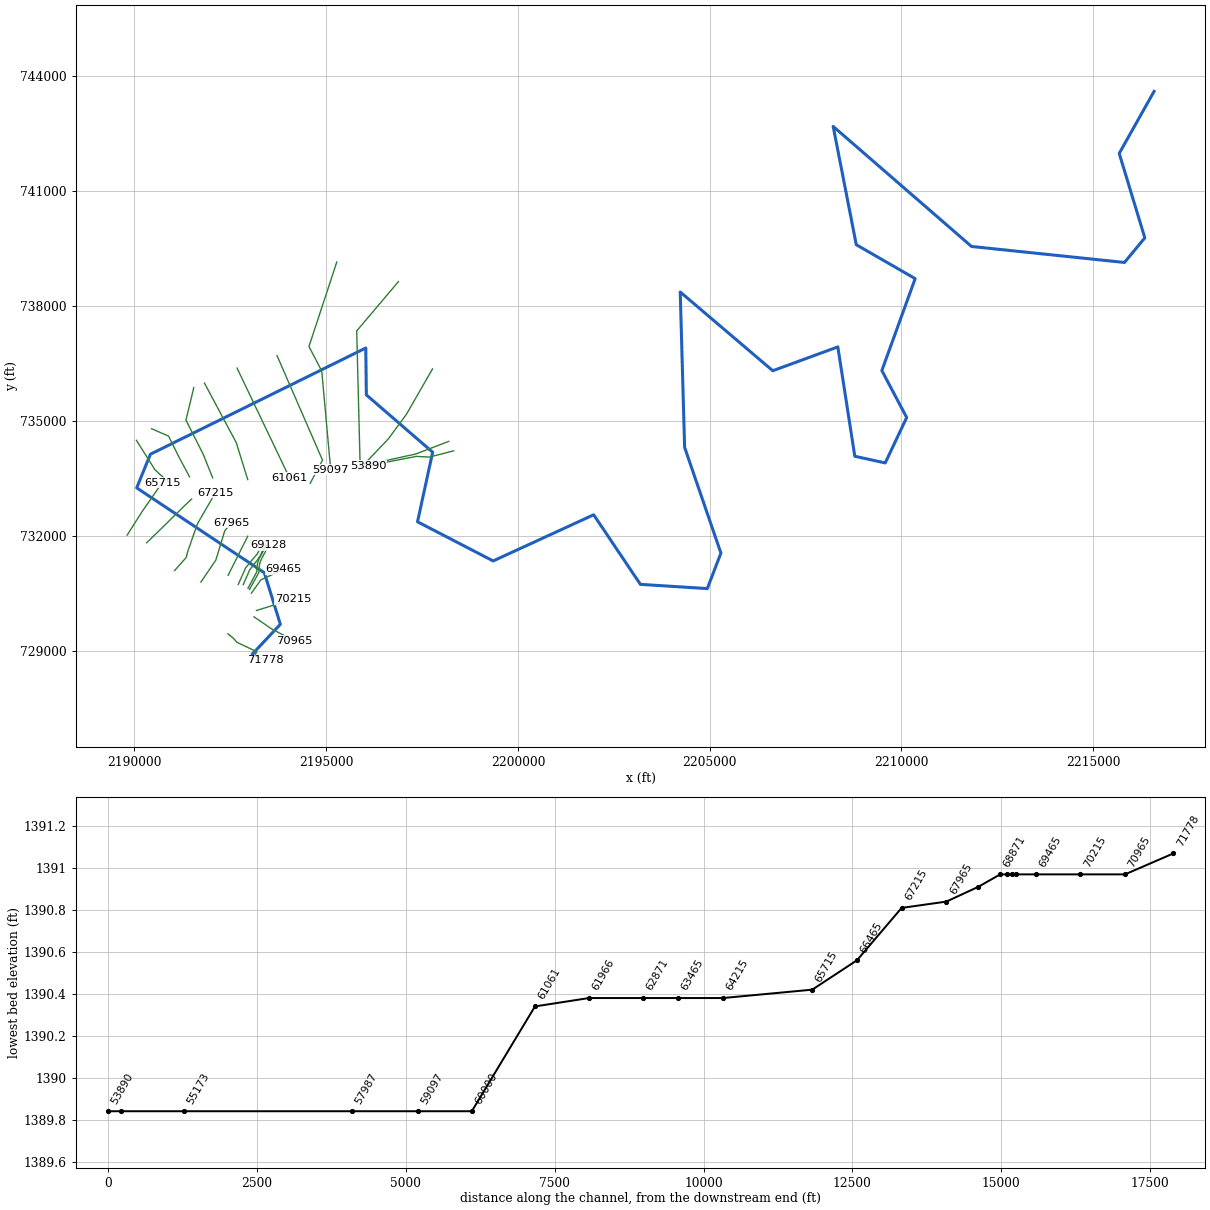
--- BUCKHANR_L.prj (project) ---

Proj Title=BUCKHANR_L
Current Plan=p01
Default Exp/Contr=0,0
English Units
Geom File=g01
Flow File=f01
Plan File=p01
BEGIN DESCRIPTION:
---------- MODELED AS PART OF WVEMD CTP PROGRAM, 2023----------
Stream Name: Buckhannon River (Lower)
Flood Zone:  AFH
Upshur County, WV
HEC-RAS Version: RAS 6.3
Vertical Datum: NAVD88
Projection: NAD 1983 StatePlane West Virginia S FIPS 4702 (US Feet)
Terrain: 1-meter LIDAR (FEMA Region III 3DEP collected 2016-2018)
Land Use: 2019 NLCD
Hydrologic Method:
Gage-Weighted WV 2010 RRE
Additional Model Notes:
DS extent at county boundary. US limit at flood zone change.
END DESCRIPTION:
DSS Export Rating Curves= 0
DSS Export Rating Curve Sorted= 0
DSS Export Volume Flow Curves= 0
DXF OffsetX= 0
DXF OffsetY= 0
DXF ScaleX= 0
DXF ScaleY= 0

--- BUCKHANR_L.p01 (plan) ---

Plan Title=Floodplain
Program Version=6.31
Short Identifier=Floodplain
Geom File=g01
Flow File=f01
Subcritical Flow
K Sum by GR= 0
Std Step Tol= 0.01
Critical Tol= 0.01
Num of Std Step Trials= 20
Max Error Tol= 0.3
Flow Tol Ratio= 0.001
Split Flow NTrial= 30
Split Flow Tol= 0.02
Split Flow Ratio= 0.02
Log Output Level= 0
Friction Slope Method= 1
Unsteady Friction Slope Method= 2
Unsteady Bridges Friction Slope Method= 1
Parabolic Critical Depth
Global Vel Dist= 0 , 0 , 0
Global Log Level= 0
CheckData=True
Encroach Param=-1 ,0,0, 0
Mapping Interval=1HOUR
Computation Time Step Use Courant=        0
Computation Time Step Use Time Series=    0
Computation Time Step Count To Double=0
Computation Time Step Max Doubling=0
Computation Time Step Max Halving=0
Computation Time Step Residence Courant=0
Run HTab= 0
Run UNet= 0
Run Sediment= 0
Run PostProcess= 0
Run WQNet= 0
Run RASMapper=-1
UNET Theta= 0
UNET Theta Warmup= 0
UNET ZTol= 0
UNET ZSATol= 0
UNET MxIter= 0
UNET Max Iter WO Improvement= 0
UNET MaxInSteps= 0
UNET DtIC= 0
UNET DtMin= 0
UNET MaxCRTS= 0
UNET WFStab= 0
UNET SFStab= 0
UNET WFX= 1
UNET SFX= 1
UNET Gravity=32.17405
UNET 1D Methodology=Finite Difference
UNET DSS MLevel= 1
UNET Pardiso=0
UNET DZMax Abort= 0
UNET Use Existing IB Tables= 0
UNET Froude Reduction=False
UNET Froude Limit= 0
UNET Froude Power= 0
UNET D1 Cores= 0
UNET WindReference=Eulerian
UNET WindDragFormulation=Hsu (1988)
UNET D2 Coriolis=0
UNET D2 Cores= 0
UNET D2 Theta= 1
UNET D2 Theta Warmup= 1
UNET D2 Z Tol= 0.01
UNET D2 Volume Tol= 0.01
UNET D2 Max Iterations= 20
UNET D2 Equation= 0
UNET D2 RampUpFraction=0.1
UNET D2 TimeSlices= 1
UNET D2 Turbulence Formulation=Non-Conservative (original)
UNET D2 Eddy Viscosity=0.3
UNET D2 Transverse Eddy Viscosity=0.1
UNET D2 Smagorinsky Mixing=0
UNET D2 BCVolumeCheck=0
UNET D2 Cores=0
UNET D2 SolverType=PARDISO (Direct)
UNET D2 Minimum Iterations= 3
UNET D2 Maximum Iterations= 30
UNET D2 Restart Number= 10
UNET D2 Relaxation Coeff=1.3
UNET D2 SOR Precondition Iterations= 10
UNET D2 ILUT Maximum Fill= 8
UNET D2 ILUT Tolerance=1E-08
UNET D2 Convergence Tolerance=0.00001
UNET D1D2 MaxIter= 0
UNET D1D2 ZTol=0.01
UNET D1D2 QTol=0.1
UNET D1D2 MinQTol=1
Write IC File= 0
Write IC File at Fixed DateTime=0
Write IC File at Sim End=0
Echo Input=False
Echo Parameters=False
Echo Output=False
Write Detailed= 0
HDF Write Warmup=0
HDF Write Time Slices=0
HDF Flush=0
HDF Compression= 1
HDF Chunk Size= 1
HDF Spatial Parts= 1
HDF Use Max Rows=0
HDF Fixed Rows= 1
Calibration Method= 0
Calibration Iterations= 20
Calibration Max Change=0.05
Calibration Tolerance=0.2
Calibration Maximum=1.5
Calibration Minimum=0.5
Calibration Optimization Method= 1
WQ AD Non Conservative
WQ ULTIMATE=-1
WQ Max Comp Step=1HOUR
WQ Output Interval=15MIN
WQ Output Selected Increments= 0
WQ Create Restart=0
WQ Fixed Restart=0
WQ System Summary=0
WQ Write To DSS=0
Sorting and Armoring Iterations= 10
XS Update Threshold= 0.02
Bed Roughness Predictor= 0
Hydraulics Update Threshold= 0.02
Energy Slope Method= 1
Volume Change Method= 1
Sediment Retention Method= 0
Sediment TS Multiplier= 1
Warm Up Method= 0
XS Weighting Method= 0
Number of US Weighted Cross Sections= 1
Number of DS Weighted Cross Sections= 1
Upstream XS Weight=0
Main XS Weight=1
Downstream XS Weight=0
Number of DS XS's Weighted with US Boundary= 1
Upstream Boundary Weight= 1
Weight of XSs Associated with US Boundary= 0
Number of US XS's Weighted with DS Boundary= 1
Downstream Boundary Weight= 0.5
Weight of XSs Associated with DS Boundary= 0.5
Percentile Method= 0
Sediment Output Level= 3
Mass or Volume Output= 0
Output Increment Type= 1
Profile and TS Output Increment= 1
Transport Output Increment 1
XS Output Flag= 0
XS Output Increment= 10
Read HDF5 Sediment Hotstart= 0
Sediment Hotstart Type= 0
Write Gradation File= 0
Read Gradation Hotstart= 0
Write HDF5 File= 1
Write Binary Output= 1
Write DSS Sediment File= 0
DSS Sediment Output Type= 1
SV Curve= 0
Specific Gage Flag= 0
Subcell Erosion Methods= 0
Subcell Deposition Methods= 0
Advection Scheme= 1
Matrix Solver= 0
Implicit Weighting Factor= 1
Maximum Outer Loop Convergence Iterations= 5
Convergence Maximum Absolute= 0.001
Convergence RMSE= 0.0001
Grain Fractions Max Abs Error= 0.001
Max Subgrid Regions= 1
Max Subgrid Length Scale= 3.402823E+38
Initial Layer Thickness= 3.402823E+38
Min Layer Thickness= 3.402823E+38
Max Layer Thickness= 3.402823E+38
Number of Layers= 5

--- BUCKHANR_L.f01 (steady flow) ---

Flow Title=Flows
Program Version=6.30
Number of Profiles= 1
Profile Names=01pct
River Rch & RM=BUCKHANR_L,Main,71778
   15500
Boundary for River Rch & Prof#=BUCKHANR_L,Main            , 1
Up Type= 0
Dn Type= 3
Dn Slope=0.0006
DSS Import GetInterval= 0
DSS Import GetPeak= 0
DSS Import FillOption= 0

--- BUCKHANR_L.g01 (geometry) ---

Geom Title=Geometry
Program Version=6.31

River Reach=BUCKHANR_L      ,Main
Reach XY= 30
 2193076.8295914728926.880333768      2193804.66      729701.288
     2193386.861      731046.745     2190058.546      733261.825
      2190415.85      734139.404     2196031.873      736911.616
     2196047.355      735687.407     2197776.014      734192.744
     2197381.623       732376.52     2199353.979      731354.514
     2201975.154      732559.493      2203193.01       730743.64
     2204938.581      730633.066     2205292.881      731559.693
     2204346.794      734317.741     2204231.928      738373.799
     2206645.406      736318.112       2208342.1      736940.719
     2208784.338      734086.263     2209578.271      733912.819
     2210136.977      735097.165      2209489.76      736323.206
     2210358.897       738721.86      2208823.17      739606.679
     2208220.194      742694.101     2211828.778       739561.15
     2215816.328      739143.609     2216347.477      739785.903
     2215679.599      741989.7372216588.49291593 743608.34297595

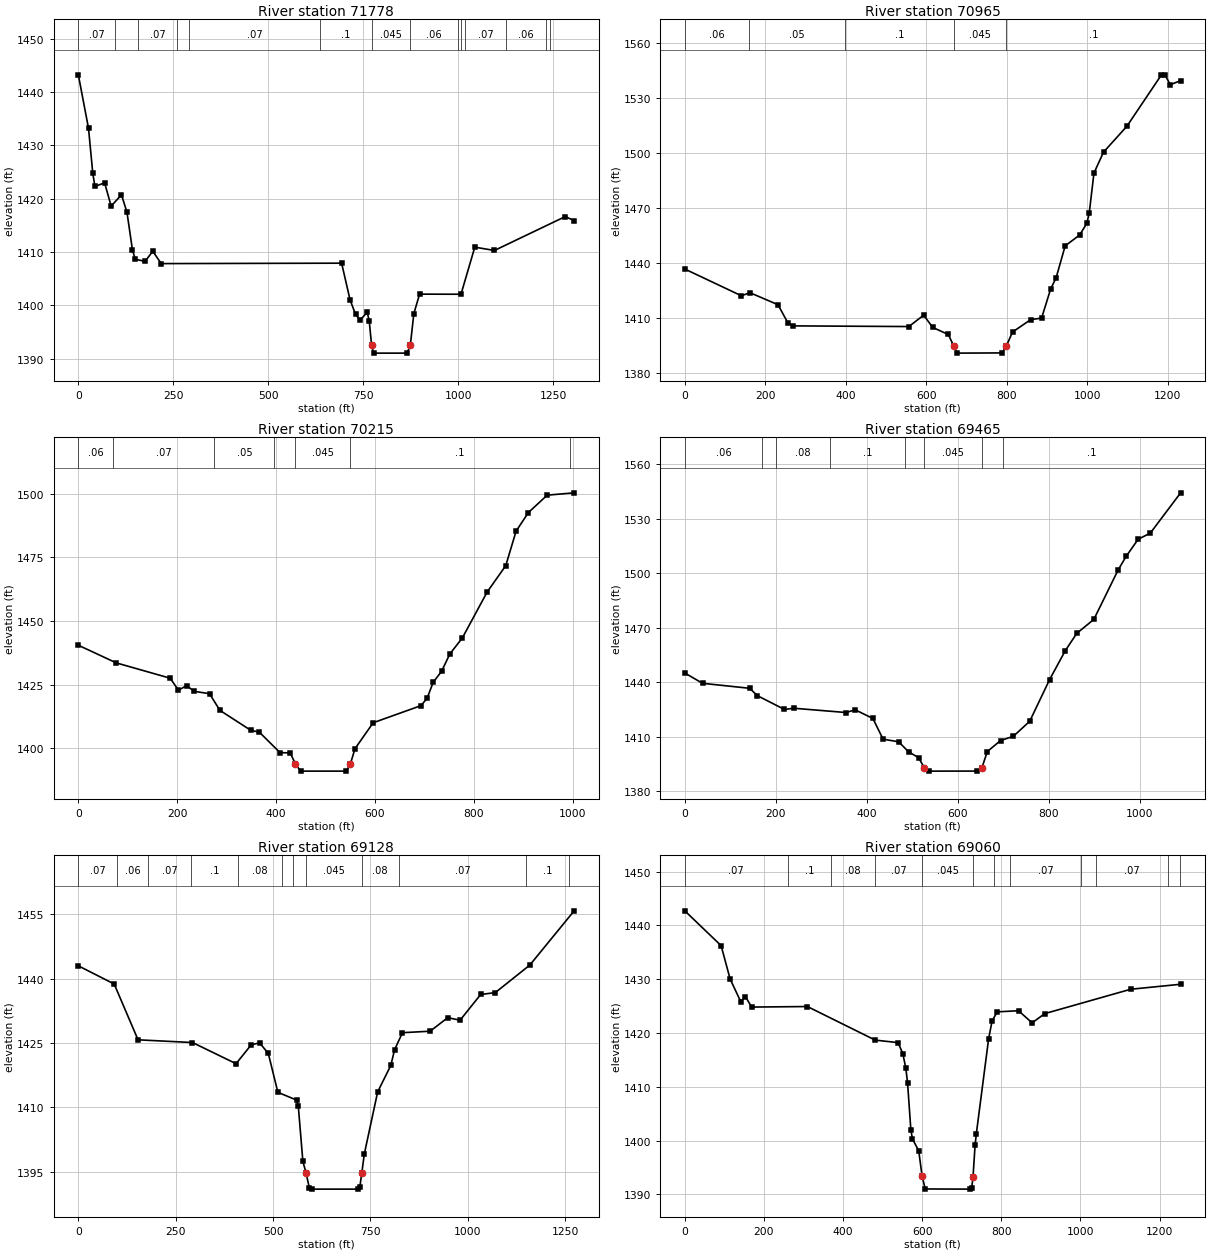
Type RM Length L Ch R = 1 ,71778   ,805.4,812.8,816.5
XS GIS Cut Line= 6
2192437.39895672729452.3038423062192577.13096434729340.440974325
2192672.91691431729230.1816471962193189.80109625728986.443839088
2193139.21040717728889.7950724362193407.56353033728761.097925276
#Sta/Elev= 30
       0  1443.2    26.8 1433.18    38.1 1424.74    43.7 1422.29    69.2 1422.97
    86.4 1418.61   113.6 1420.72   128.1 1417.45   142.5 1410.41   149.9 1408.65
   175.8 1408.26   196.1 1410.16   218.3 1407.84   693.4 1407.92   715.6 1401.05
   730.1 1398.33     742 1397.28     761 1398.71   766.2 1397.05   772.2 1392.62
   777.5 1391.07   865.9 1391.07   874.4 1392.61   883.6 1398.47   898.7 1402.12
  1007.8  1402.1  1044.1 1410.92  1095.9  1410.3  1282.4 1416.651305.802 1415.88
#Mann= 14 ,-1,0
       0     .07       0   96.65     .08       0  156.65     .07       0
  259.93     .06       0  292.66     .07       0   637.2      .1       0
   772.2    .045       0   874.4     .06       0  998.67      .1       0
 1007.76     .06       0 1017.76     .07       0 1126.43     .06       0
 1231.68     .07       0 1241.68      .1       0
Bank Sta=772.2,874.4
XS Rating Curve= 0 ,0
Exp/Cntr(USF)=0,0
Exp/Cntr=0.3,0.1

Type RM Length L Ch R = 1 ,70965   ,683.1,750,813.9
XS GIS Cut Line= 6
2193116.92937381729896.515045037  2193371.768351729722.465156928
2193465.94795267729657.1952743382193542.41728793729601.011987761
2193618.69535059729558.0343834162194174.89371325729269.548739925
#Sta/Elev= 30
       0 1436.86   140.7 1422.26   161.9 1423.95   231.6 1417.38   255.8 1407.65
   268.3 1405.84   556.8 1405.47   593.6 1411.68   616.3 1404.97   654.8 1401.14
668.34241394.889     677 1390.97   788.4 1391.09798.6424 1394.71   814.6 1402.51
   859.6 1409.25   886.7 1410.09   909.2 1425.97   922.7 1432.04   945.3 1449.52
   981.3 1455.42     999 1461.77    1005 1467.24  1016.8 1489.22  1040.6 1500.65
  1098.5 1514.72  1184.1 1542.68  1193.1 1542.83  1206.6 1537.44  1232.2 1539.67
#Mann= 5 ,-1,0
       0     .06       0     160     .05       0   398.6      .1       0
668.3424    .045       0798.6424      .1       0
Bank Sta=668.3424,798.6424
XS Rating Curve= 0 ,0
Exp/Cntr(USF)=0,0
Exp/Cntr=0.3,0.1

Type RM Length L Ch R = 1 ,70215   ,738.1,750,762.1
XS GIS Cut Line= 6
 2193182.8376265730061.3453846722193276.79642808730090.699984759
2193542.26735385730173.6378110052193613.85480909730196.003251836
2193709.30507751730225.8234021662194140.32258818730360.481269345
#Sta/Elev= 30
       0 1440.48    76.8 1433.53   185.8 1427.51   202.6 1422.79   219.3 1424.62
   233.9 1422.36   265.4 1421.43   286.4 1414.86   349.2 1406.99     366 1406.33
   407.9 1398.26   428.8 1398.12  439.091393.819   449.8 1390.97     542 1390.97
   550.1 1393.62   559.7 1399.79   596.5    1410   692.9  1416.7   705.4 1419.54
     718 1425.94   734.8 1430.19   751.5 1437.02   776.9 1443.35     827 1461.38
   864.7 1471.77   885.6 1485.33   910.4 1492.63   948.5 1499.49  1003.1 1500.41
#Mann= 7 ,-1,0
       0     .06       0      70     .07       0  275.31     .05       0
  396.56      .1       0  439.09    .045       0   550.1      .1       0
  994.69     .05       0
Bank Sta=439.09,550.1
XS Rating Curve= 0 ,0
Exp/Cntr(USF)=0,0
Exp/Cntr=0.3,0.1

Type RM Length L Ch R = 1 ,69465   ,241.2,336.5,419.1
BEGIN DESCRIPTION:
Structure XS 4
END DESCRIPTION:
XS GIS Cut Line= 6
2193050.01648656 730513.269365792193296.54166103730863.255333679
2193330.55321035730874.1200058462193488.58471842730949.292427674
2193635.32917559731019.0951095822193896.36408658731143.263824508
#Sta/Elev= 30
       0 1445.04      39 1439.36   142.7 1436.61   159.4 1432.58   219.1 1424.96
   239.7 1425.62   354.6 1423.26   374.7 1424.76   413.6 1419.99   436.1 1408.55
   470.3 1407.15   492.2 1401.58   514.3 1398.38526.81091392.686   536.3 1390.97
   642.8    1391653.41091392.877   665.4 1401.77   694.4 1407.84   722.5 1410.15
   758.5 1418.43   802.2 1441.38   836.5 1457.24     862 1466.89   899.6 1474.59
   952.8 1501.74   970.6 1509.32   997.1 1518.76  1023.7 1522.11  1090.4 1544.32
#Mann= 8 ,-1,0
       0     .06       0     170     .05       0     200     .08       0
     320      .1       0   483.8     .07       0526.8109    .045       0
653.4109     .06       0   698.8      .1       0
Bank Sta=526.8109,653.4109
XS Rating Curve= 0 ,0
Exp/Cntr(USF)=0,0
Exp/Cntr=0.3,0.1

Type RM Length L Ch R = 1 ,69128   ,83.4,68.7,59.3
BEGIN DESCRIPTION:
Structure XS 3
END DESCRIPTION:
XS GIS Cut Line= 6
2193000.52783435730612.5260643832193248.05366702731061.166636095
2193242.42807992731132.8928716982193266.33682512731289.002913892
2193304.30953808731390.263481802 2193501.2050868731764.365024358
#Sta/Elev= 30
       0 1442.99    92.1 1438.75   153.3 1425.75   293.1 1425.12     405 1420.19
   443.9 1424.58   465.4 1425.05   487.8 1422.58   512.4 1413.52   560.6 1411.71
   564.8 1410.33   576.6 1397.41   584.6 1394.81   593.1 1391.29   600.2 1390.97
   718.2 1390.97     723 1391.55     728 1394.81   734.4 1399.18   768.7 1413.64
   802.3 1419.77   812.2 1423.47   832.2 1427.41   903.4 1427.76   948.6 1430.91
   980.3 1430.32  1033.1 1436.31  1070.7 1436.75  1159.3 1443.16  1273.2  1455.8
#Mann= 12 ,-1,0
       0     .07       0     100     .06       0     180     .07       0
     290      .1       0     410     .08       0  522.39     .06       0
  552.39     .07       0   584.6    .045       0     728     .08       0
  822.27     .07       0 1150.42      .1       0 1260.42     .06       0
Bank Sta=584.6,728
XS Rating Curve= 0 ,0
Exp/Cntr(USF)=0,0
Exp/Cntr=0.3,0.1

Type RM Length L Ch R = 1 ,69060   ,122.6,78.4,41.9
BEGIN DESCRIPTION:
Structure XS 2
END DESCRIPTION:
XS GIS Cut Line= 6
  2192961.851923730644.1699918552193193.90739113731078.746595802
2193188.28180402731150.4728314052193212.19054922731306.582873599
2193250.16326219731407.843441509 2193447.0588109731781.944984065
#Sta/Elev= 30
       0  1442.7    91.8 1436.23   114.5 1430.04   141.4 1425.82   153.2 1426.77
   168.9 1424.81   309.9 1424.91   481.3 1418.67   539.2  1418.2   551.3 1416.11
   558.7 1413.44   563.1 1410.78   571.4 1402.04   575.4 1400.31   591.4 1398.09
   599.7 1393.44   607.8    1391   720.9 1390.97   725.3 1391.24  728.651393.288
   733.8 1399.12     737 1401.29   768.1 1418.95   776.6 1422.15   789.4 1423.92
   843.6 1424.13   877.9 1421.88   910.2  1423.6    1127 1428.12  1253.4 1429.05
#Mann= 12 ,-1,0
       0     .07       0     260      .1       0     370     .08       0
     480     .07       0   599.7    .045       0  728.65     .08       0
  782.53     .06       0  822.53     .07       0 1000.68     .05       0
 1040.68     .07       0 1220.68     .05       0 1250.68     .06       0
Bank Sta=599.7,728.65
XS Rating Curve= 0 ,0
Exp/Cntr(USF)=0,0
Exp/Cntr=0.3,0.1

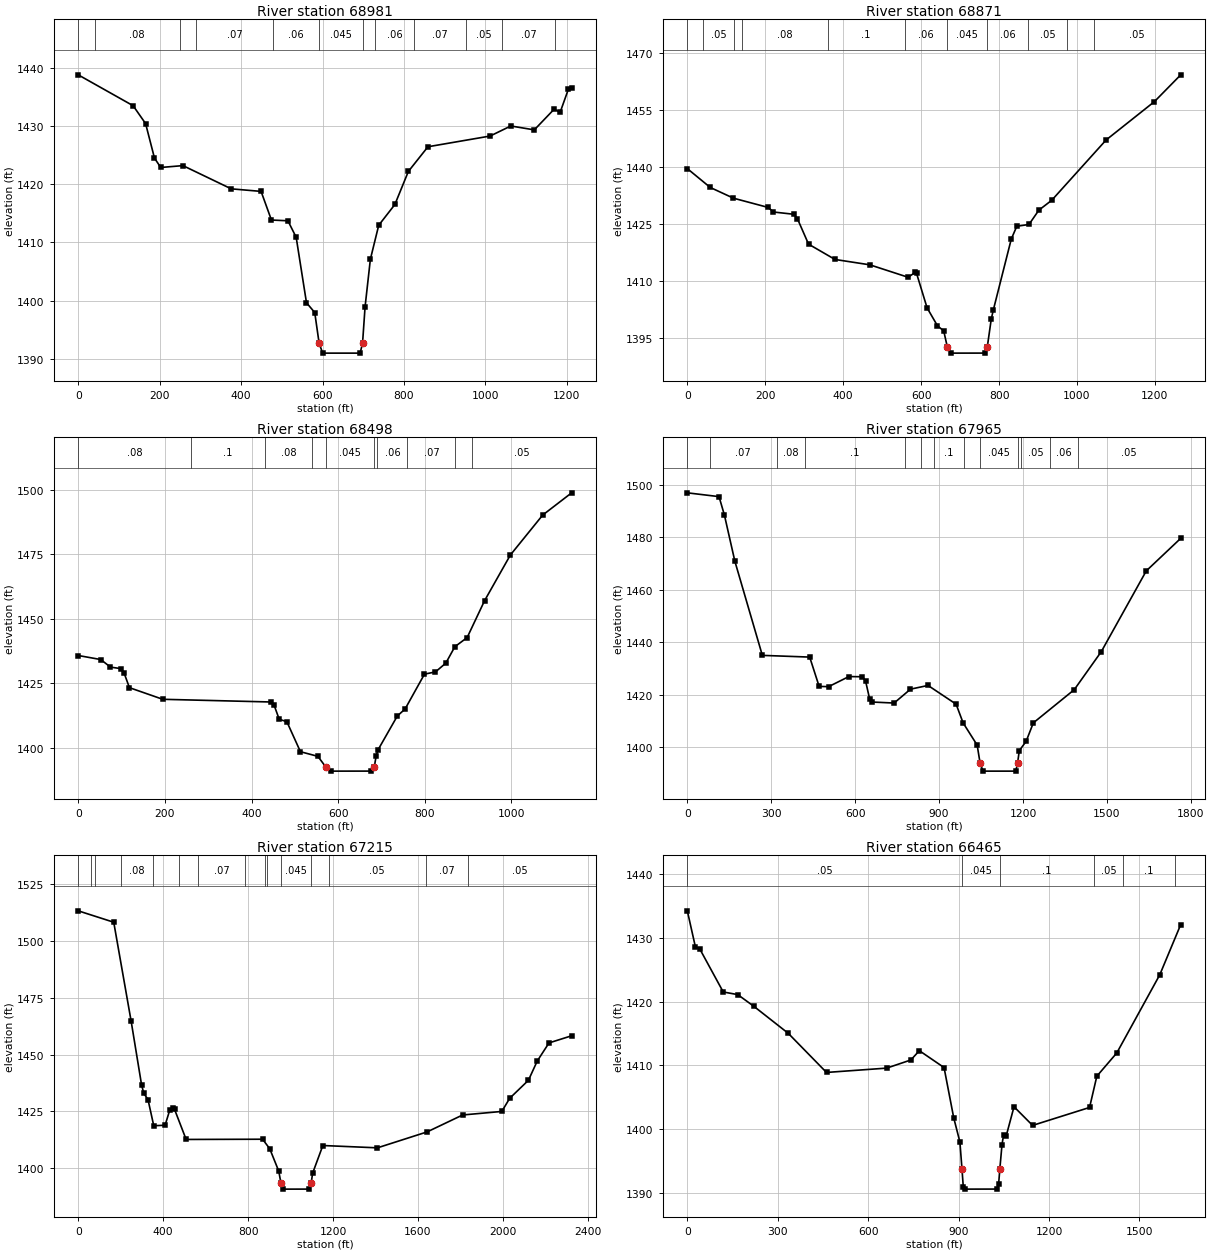
Type RM Length L Ch R = 1 ,68981   ,111.8,110.2,108.1
BEGIN DESCRIPTION:
Structure XS 3
END DESCRIPTION:
XS GIS Cut Line= 5
2192836.68260989 730737.617244342193004.82515784731121.407298023
2193217.03480479731394.0920063612193285.01064898731501.603226611
2193418.46207645731792.571093043
#Sta/Elev= 30
       0 1438.79   134.9 1433.48   165.5 1430.41   187.3 1424.48   202.7 1422.87
   257.2 1423.19   375.8  1419.2   449.1 1418.76   474.5 1413.84     515 1413.71
   535.3 1410.87   560.6 1399.63   580.9 1397.94  591.57  1392.7   600.3 1390.97
   692.4 1390.97  698.32  1392.7   704.5 1398.93   717.5  1407.1     738 1412.94
   777.7 1416.51   810.8 1422.19   858.9 1426.43  1011.5 1428.27  1062.4    1430
  1120.1 1429.33    1169  1432.9  1183.4 1432.32  1203.7  1436.3  1211.8 1436.61
#Mann= 12 ,-1,0
       0     .05       0      40     .08       0     250      .1       0
     290     .07       0  479.01     .06       0  591.57    .045       0
  698.32     .08       0  729.01     .06       0  824.54     .07       0
  951.73     .05       0 1041.73     .07       0 1171.73     .05       0
Bank Sta=591.57,698.32
XS Rating Curve= 0 ,0
Exp/Cntr(USF)=0,0
Exp/Cntr=0.3,0.1

Type RM Length L Ch R = 1 ,68871   ,358.7,373.3,391
BEGIN DESCRIPTION:
Structure XS 2
END DESCRIPTION:
XS GIS Cut Line= 6
2192705.57517706730739.3361737342192900.12673114731176.100505999
2193132.96353081731458.9425243892193193.90739113731526.137037045
2193232.97396825731593.3315497022193341.42278635731822.261691658
#Sta/Elev= 30
       0 1439.49    58.9 1434.53   118.5 1431.71   207.8 1429.27     221 1428.08
   273.5 1427.48   282.3 1426.37   311.1 1419.63     379  1415.6   468.4 1414.19
   566.3 1410.93   585.2 1412.19   588.3 1411.93   615.3 1402.87   641.9 1398.16
     658 1396.81   667.1 1392.64   676.4 1390.97   763.1 1390.98   769.7 1392.53
     780 1399.95   785.2 1402.29   831.3 1420.96   845.5 1424.33   876.7  1424.8
   902.1 1428.56   935.2 1431.17  1074.7 1447.02  1198.7 1457.11  1266.2 1464.15
#Mann= 11 ,-1,0
       0     .06       0      40     .05       0     120     .07       0
     140     .08       0     360      .1       0  558.14     .06       0
   667.1    .045       0   769.7     .06       0  874.49     .05       0
   975.2     .06       0 1042.93     .05       0
Bank Sta=667.1,769.7
XS Rating Curve= 0 ,0
Exp/Cntr(USF)=0,0
Exp/Cntr=0.3,0.1

Type RM Length L Ch R = 1 ,68498   ,521.6,532.9,550.7
XS GIS Cut Line= 2
2192444.10648837730982.6256675062192954.27632957732000.821779151
#Sta/Elev= 30
       0 1435.74    52.1 1434.17    74.4 1431.24    98.4 1430.66   105.8 1428.99
   118.2 1423.27   195.2 1418.76   446.1 1417.71     452 1416.54   463.9 1411.03
   481.6 1410.07   512.9 1398.44   553.2 1396.64   571.6 1392.48   584.5 1390.91
   675.6 1390.92  683.52 1392.66   687.5 1396.65   691.9 1399.13   736.6  1412.3
   754.5    1415   799.2 1428.51   824.6 1429.38   848.5 1432.79   869.3 1439.14
   897.7 1442.69   937.9 1456.98   997.5 1474.71  1072.1 1490.19  1138.9 1498.81
#Mann= 10 ,-1,0
       0     .08       0     260      .1       0     430     .08       0
     540     .05       0   571.6    .045       0  683.52    .025       0
     690     .06       0     760     .07       0     870     .06       0
     910     .05       0
Bank Sta=571.6,683.52
XS Rating Curve= 0 ,0
Exp/Cntr(USF)=0,0
Exp/Cntr=0.3,0.1

Type RM Length L Ch R = 1 ,67965   ,753.2,750,746.1
XS GIS Cut Line= 6
2191732.58710115730803.4359605852192120.53266451731373.941840842
2192253.04125775731807.2592156682192300.56150392731962.655886501
2192356.30614309732144.9478447592192530.43961254732348.606360961
#Sta/Elev= 30
       0 1496.92   113.4 1495.47   132.7 1488.41     170 1470.84   268.2 1434.96
   437.5 1434.31   471.3 1423.13   505.2 1423.04   577.7 1426.89   626.1 1426.81
   637.3 1425.19   651.7  1418.4   660.8 1417.18   739.3 1416.79   797.9 1422.08
   860.6  1423.5     961 1416.36   986.1 1409.21  1036.3 1400.75  1046.71393.891
  1057.2 1390.84  1174.3 1390.84  1180.6 1393.77  1186.9 1398.66  1211.2 1402.17
  1237.1 1409.24  1383.5  1421.9  1480.2 1436.41  1640.9 1467.17  1764.1 1479.58
#Mann= 13 ,-1,0
       0     .08       0      80     .07       0     320     .08       0
     420      .1       0  779.91     .08       0  836.79     .07       0
  880.54      .1       0  988.04    .025       0  1046.7    .045       0
  1180.6      .1       0 1193.04     .05       0 1298.04     .06       0
 1395.54     .05       0
Bank Sta=1046.7,1180.6
XS Rating Curve= 0 ,0
Exp/Cntr(USF)=0,0
Exp/Cntr=0.3,0.1

Type RM Length L Ch R = 1 ,67215   ,784.4,750,699.1
XS GIS Cut Line= 6
2191046.40951679731102.7821820122191348.68004957731444.388744864
2191387.51411742731594.1169254182191620.76299475 732264.04832834
2191658.83345668732353.3719685822192113.62593922733137.343583998
#Sta/Elev= 30
       0 1513.33   167.3 1508.31   249.5 1464.61   298.4 1436.68     309 1432.94
   328.6 1430.26   355.7 1418.72   409.1 1418.93   430.8 1425.54     445 1426.62
   453.5 1425.96   508.2 1412.68   868.3 1412.78   902.1 1408.56   944.4 1398.72
  954.66 1393.45   965.6 1390.81  1088.4 1390.821096.8841393.362  1103.8  1397.8
    1152 1410.01    1409 1408.99  1643.2 1416.01  1810.1 1423.45  1994.7 1425.01
  2032.1 1430.82    2120 1438.72  2161.6  1447.2    2217 1455.18  2323.6 1458.32
#Mann= 15 ,-1,0
       0      .1       0      60     .08       0      80      .1       0
     200     .08       0     350     .07       0  476.14     .05       0
  566.14     .07       0   787.7     .06       0  881.45     .07       0
  888.95      .1       0  954.66    .045       01096.884      .1       0
 1178.95     .05       0 1637.29     .07       0 1837.29     .05       0
Bank Sta=954.66,1096.884
XS Rating Curve= 0 ,0
Exp/Cntr(USF)=0,0
Exp/Cntr=0.3,0.1

Type RM Length L Ch R = 1 ,66465   ,734.1,750,765.5
XS GIS Cut Line= 6
2190317.12134381731827.7051174332190725.93506001732225.369599923
2190861.87409259732359.0051594232190924.27226175732420.346572176
2191300.88994683732790.5827083442191490.59927474732969.143130606
#Sta/Elev= 30
       0 1434.28    26.6 1428.66    42.3 1428.21   119.2 1421.53   167.3 1421.12
     221 1419.27   334.8 1415.04   461.8 1408.89   661.3 1409.57   741.7 1410.85
   769.8 1412.31   851.8 1409.66   883.9 1401.76   904.4 1397.96   911.2 1393.77
   915.6 1390.92   921.2 1390.56  1027.2 1390.57  1032.8 1391.32 1036.98 1393.79
  1044.1 1397.57  1049.3 1399.07  1058.3 1398.97  1083.9  1403.5  1145.6 1400.57
  1334.6 1403.39  1358.7  1408.3    1425 1411.96  1567.5 1424.23  1637.1 1432.13
#Mann= 6 ,-1,0
       0     .05       0   911.2    .045       0 1036.98      .1       0
  1349.7     .05       0 1446.57      .1       0 1616.57     .05       0
Bank Sta=911.2,1036.98
XS Rating Curve= 0 ,0
Exp/Cntr(USF)=0,0
Exp/Cntr=0.3,0.1

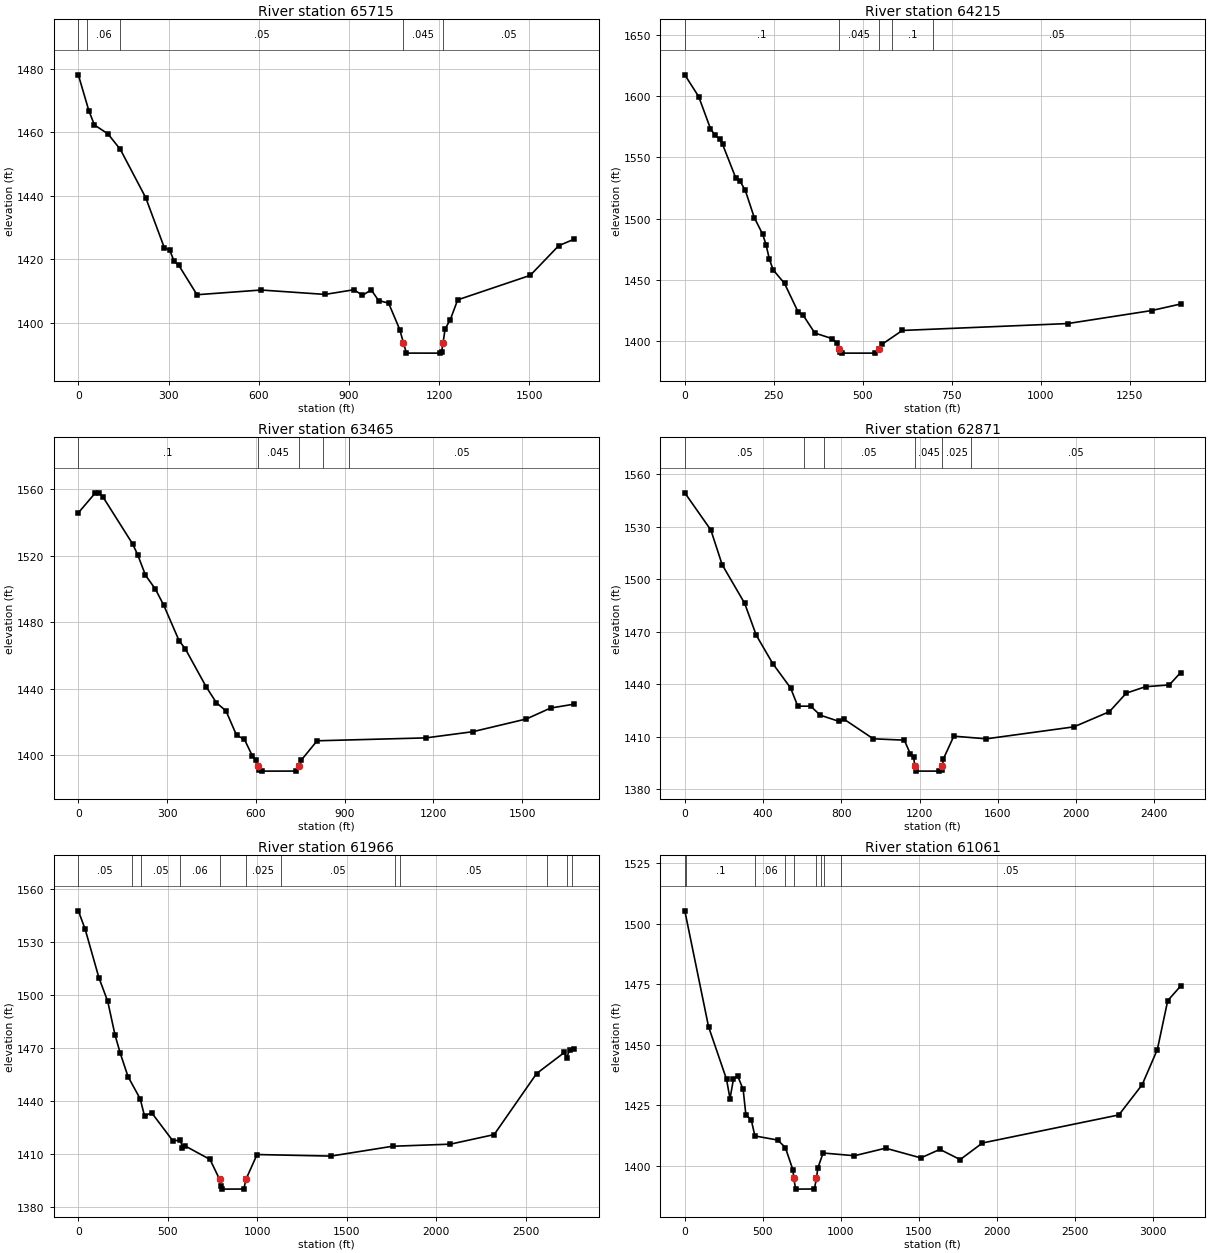
Type RM Length L Ch R = 1 ,65715   ,1667.1,1500,1350.8
XS GIS Cut Line= 6
2189809.17486424732028.0313207252190208.93904676732656.630548418
2190367.63918868732885.0333068372190510.29113434733090.338670507
2190560.21918409733162.1958102582190725.16045526733399.580506086
#Sta/Elev= 30
       0 1478.01    34.9 1466.75    53.5 1462.23    98.6 1459.42   139.8 1454.53
   224.2 1439.34   285.8 1423.66   304.4 1422.75     319 1419.26   333.6 1418.15
   394.8  1408.8   608.1 1410.28   820.7  1408.9   917.2 1410.37   945.3 1408.61
   974.5 1410.32   998.9 1406.97  1032.2 1406.17  1069.5 1397.811081.7111393.596
  1091.4 1390.43  1204.6 1390.42  1208.3  1390.71213.3111393.579  1220.3 1398.05
  1237.6 1400.98  1262.1 1407.19  1503.5  1414.9  1598.3 1424.24  1649.6 1426.28
#Mann= 5 ,-1,0
       0      .1       0      30     .06       0     140     .05       0
1081.711    .045       01213.311     .05       0
Bank Sta=1081.711,1213.311
XS Rating Curve= 0 ,0
Exp/Cntr(USF)=0,0
Exp/Cntr=0.3,0.1

Type RM Length L Ch R = 1 ,64215   ,759.2,750,743.3
XS GIS Cut Line= 6
2190050.87046526734502.2784319222190103.33361493734418.986603752
 2190251.5623211734183.6534130132190384.80221209733972.118074924
2190533.03124633 733736.784884172190892.96521675733406.849747394
#Sta/Elev= 30
       0 1617.43    39.1 1599.61    72.2 1573.45      85 1568.13    97.5 1565.04
   106.2  1560.7   143.1 1533.37   155.5 1530.53     170 1523.11   195.1 1501.03
   218.8 1487.35   228.2  1478.9   237.7 1466.91   248.3 1458.27   280.2 1447.25
     318 1424.16   332.4 1421.35   365.3 1406.78   413.6 1402.23   426.8 1398.95
   433.6 1393.63   436.2 1391.31   440.9 1390.38   535.5 1390.38  546.291393.653
   554.4 1397.64   611.1 1408.88  1075.8  1414.5  1311.5 1425.11    1393 1430.46
#Mann= 5 ,-1,0
       0      .1       0   433.6    .045       0  546.29    .025       0
  581.56      .1       0  696.56     .05       0
Bank Sta=433.6,546.29
XS Rating Curve= 0 ,0
Exp/Cntr(USF)=0,0
Exp/Cntr=0.3,0.1

Type RM Length L Ch R = 1 ,63465   ,593.3,594.1,594.7
XS GIS Cut Line= 6
2190447.98230137734804.8802483312190888.86550842734613.646319419
2190927.77750409734535.2747570132191005.60083926734378.530976012
2191162.63759868 734062.245519342191435.47676543733550.807853276
#Sta/Elev= 30
       0 1545.93    57.7 1557.98      70 1557.94    83.1 1555.54   183.3 1527.26
   200.8 1520.62   226.9 1508.39   260.6 1499.95   288.8 1490.25   340.3 1469.03
   362.1 1463.87   431.7 1441.28   466.7 1431.53     499 1426.69   534.7 1412.02
   561.5 1409.47   587.8 1399.68   599.8 1397.16  606.26 1393.45   611.7 1391.13
   619.5 1390.38   735.6 1390.41745.32841393.442   753.5 1396.99   807.1 1408.65
    1175  1410.4  1333.2 1414.12  1514.5  1421.8  1596.1 1428.36  1675.9 1430.72
#Mann= 5 ,-1,0
       0      .1       0  606.26    .045       0745.3284      .1       0
  828.07    .025       0  915.57     .05       0
Bank Sta=606.26,745.3284
XS Rating Curve= 0 ,0
Exp/Cntr(USF)=0,0
Exp/Cntr=0.3,0.1

Type RM Length L Ch R = 1 ,62871   ,901.5,904.3,904.5
XS GIS Cut Line= 4
  2191547.214558735878.8344894092191342.53331685735029.023932596
2191789.23988251734146.2474260132192040.01396726733523.444552827
#Sta/Elev= 30
       0 1549.38   133.4  1528.1     191 1508.32   306.2 1486.22   365.3 1468.04
   450.2 1451.73   540.7 1437.93   577.7  1427.5   643.5 1427.48   692.9 1422.33
   787.6 1418.84   812.2 1420.18   963.6 1408.85  1122.3 1408.07  1152.4 1400.36
  1169.8 1398.42 1175.74 1393.55  1183.3 1390.41  1300.9 1390.38  1313.3 1391.08
  1317.3 1393.54  1322.2  1397.4  1375.3 1410.35  1541.9 1408.84  1989.5 1415.68
  2170.8 1424.34    2257 1434.94  2355.4 1438.61  2476.9 1439.62  2534.9 1446.67
#Mann= 6 ,-1,0
       0     .05       0     610     .07       0     710     .05       0
 1175.74    .045       0  1317.3    .025       0 1464.11     .05       0
Bank Sta=1175.74,1317.3
XS Rating Curve= 0 ,0
Exp/Cntr(USF)=0,0
Exp/Cntr=0.3,0.1

Type RM Length L Ch R = 1 ,61966   ,909.1,905.8,901.4
XS GIS Cut Line= 3
2191825.84545061735994.0912421352192654.61432869734441.819899532
2192954.27659224733476.835987813
#Sta/Elev= 30
       0 1547.75    37.9 1537.43   114.7    1510   164.3 1496.54   205.1 1477.47
   234.3  1467.2   277.6 1454.01   345.6 1441.43   370.1 1431.61   409.1 1433.64
   528.6  1417.6     570 1418.17   581.4 1413.91   596.6  1414.8   735.6 1407.18
   788.7    1396   794.6 1392.03   803.3 1390.38   924.7 1390.44   936.5 1395.91
   998.6 1409.94  1411.2 1409.06  1755.4 1414.62  2078.7 1415.81  2323.2 1421.22
  2560.3 1455.74  2715.3 1467.65  2727.9 1464.33  2744.6 1469.33  2770.1 1469.43
#Mann= 12 ,-1,0
       0     .05       0     300      .1       0     350     .05       0
     570     .06       0   788.7    .045       0   936.5    .025       0
    1130     .05       0 1769.66     .06       0 1799.66     .05       0
 2619.66      .1       0 2729.66     .05       0 2759.66     .06       0
Bank Sta=788.7,936.5
XS Rating Curve= 0 ,0
Exp/Cntr(USF)=0,0
Exp/Cntr=0.3,0.1

Type RM Length L Ch R = 1 ,61061   ,1064.3,1060.2,1057.9
XS GIS Cut Line= 2
2192675.48635801736386.6309152452194045.24146846733518.505191015
#Sta/Elev= 30
       0  1505.4   152.3 1457.47   267.6 1435.74   289.7 1427.73   311.9  1435.8
   338.5 1437.19     374 1431.58   391.6 1421.04   425.9 1419.02   449.3 1412.33
   595.6 1410.63   644.4 1407.55   693.1 1398.28  698.69 1394.76   710.8 1390.34
   830.5  1390.4   843.91394.769   852.7 1399.05   886.6 1405.27  1087.6 1404.15
  1287.1 1407.27  1513.2 1403.25  1635.2 1406.78  1765.1 1402.55  1907.7 1409.41
  2782.6 1421.02  2931.7 1433.49  3029.2 1448.06  3095.7 1468.28  3178.4 1474.28
#Mann= 9 ,-1,0
       0     .05       0      10      .1       0     450     .06       0
     640     .05       0  698.69    .045       0   843.9     .05       0
     870    .025       0     890      .1       0    1000     .05       0
Bank Sta=698.69,843.9
XS Rating Curve= 0 ,0
Exp/Cntr(USF)=0,0
Exp/Cntr=0.3,0.1

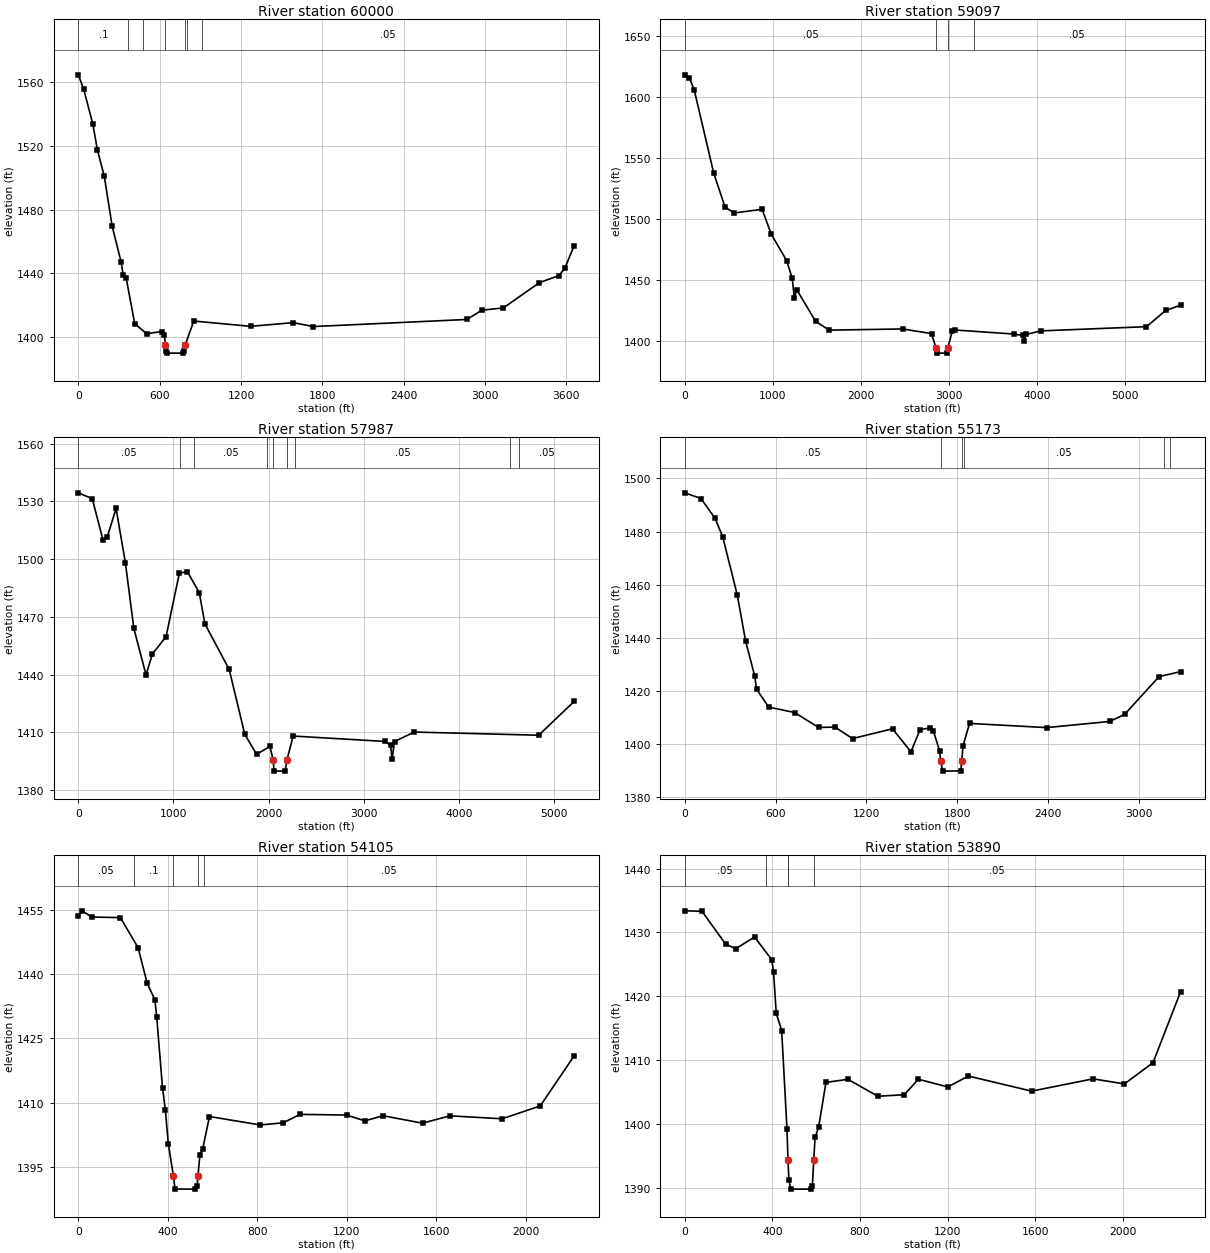
Type RM Length L Ch R = 1 ,60000   ,895.8,903.6,908.4
XS GIS Cut Line= 3
2193717.27193497736714.6004487342194903.82888171 733985.60461864
2194583.54288397733383.427276353
#Sta/Elev= 30
       0 1564.58    39.8 1555.52   106.6 1533.78   141.1 1517.26   191.8 1500.78
   249.5 1469.56   315.6 1446.98   331.6 1438.71   352.9 1437.04   415.9 1408.36
   503.1 1402.08   620.9  1403.4     634 1401.26   642.7 1395.07   647.1 1391.41
   655.8 1389.84   773.6 1389.84   782.3 1390.87  789.31 1395.06   851.4    1410
  1270.5 1406.66  1584.9 1408.98    1733 1406.53  2867.2 1410.97  2975.8 1416.79
  3135.6 1418.22    3401 1434.08  3545.8 1438.54  3588.1 1442.98  3657.8 1457.33
#Mann= 7 ,-1,0
       0      .1       0     370     .06       0     480     .05       0
   642.7    .045       0  789.31    .025       0     800      .1       0
     910     .05       0
Bank Sta=642.7,789.31
XS Rating Curve= 0 ,0
Exp/Cntr(USF)=0,0
Exp/Cntr=0.3,0.1

Type RM Length L Ch R = 1 ,59097   ,1149.1,1109.8,1065
XS GIS Cut Line= 4
2195276.23204179739155.4056664092194550.47059394 736950.40734265
2194883.88785409736312.0923541962195117.38155515733735.271622343
#Sta/Elev= 30
       0 1618.39    52.9 1615.65   107.6 1605.81   328.1 1537.75   457.1 1509.68
   562.4 1504.94   878.3 1507.97   979.3 1487.83  1156.2  1465.8  1219.4 1451.28
  1243.8 1435.27  1269.1 1442.09  1484.6    1416  1637.8 1408.71  2471.9 1409.69
  2800.8 1405.87  2851.2 1394.26  2859.8 1389.86  2977.1 1389.84  2986.71394.256
  3035.8 1407.72  3072.6  1408.8  3740.5 1405.49  3835.7 1404.34  3851.7 1399.89
  3875.8 1405.24  4044.5 1408.11  5241.4 1411.56  5458.3 1424.85  5628.9 1429.17
#Mann= 4 ,-1,0
       0     .05       0  2851.2    .045       0  2986.7      .1       0
 3281.52     .05       0
Bank Sta=2851.2,2986.7
XS Rating Curve= 0 ,0
Exp/Cntr(USF)=0,0
Exp/Cntr=0.3,0.1

Type RM Length L Ch R = 1 ,57987   ,2859.5,2813.7,2732
XS GIS Cut Line= 3
2196883.43875815738644.1100141662195795.35159999737356.926056852
2195885.28145934733832.796957894
#Sta/Elev= 30
       0 1534.47   146.3 1531.41   259.1 1509.97   302.5  1511.3   396.7 1526.35
   495.4 1497.82   583.4    1464   711.4 1439.87     779 1450.77   922.1 1459.74
  1061.8 1492.73  1145.6 1493.52  1271.4 1482.55  1329.9 1466.39  1585.4 1442.67
  1749.2 1409.01  1873.2 1398.57  2013.3 1402.67 2046.67  1395.8  2057.3 1389.87
  2173.4 1389.84  2193.2 1395.82  2257.4 1408.07  3217.7 1405.28  3281.7 1403.28
  3297.4  1396.1  3322.7 1405.21  3529.8 1410.15  4838.2  1408.5  5210.7 1426.08
#Mann= 9 ,-1,0
       0     .05       0    1070      .1       0    1220     .05       0
 1985.46      .1       0 2046.67    .045       0  2193.2    .025       0
 2275.46     .05       0 4535.46     .08       0 4635.46     .05       0
Bank Sta=2046.67,2193.2
XS Rating Curve= 0 ,0
Exp/Cntr(USF)=0,0
Exp/Cntr=0.3,0.1

Type RM Length L Ch R = 1 ,55173   ,1117.2,1068.4,1036.1
XS GIS Cut Line= 6
2197772.08085091736366.1413077632197095.12638985735186.079229668
2197037.76069093735108.0157375042196982.24571009735032.469956845
2196617.69624235734536.3876156662195852.36127168733733.951351283
#Sta/Elev= 30
       0 1494.59   107.2 1492.45   199.4 1485.03   250.1 1478.12     347 1456.07
   401.7 1438.78   462.3 1425.57   474.1 1420.65   554.5 1413.94   725.1  1411.9
   884.1 1406.28   992.6 1406.41  1107.9 1402.09  1372.2 1405.78  1493.8 1397.11
  1554.6 1405.49  1617.9 1406.06  1642.4 1404.95  1683.7  1397.41689.7091393.665
  1703.7 1389.84  1823.2 1389.941829.609 1393.75  1838.2 1399.37  1881.1  1407.8
  2390.7 1406.22  2806.4 1408.53  2905.6 1411.19  3132.9 1425.41  3275.6 1427.29
#Mann= 6 ,-1,0
       0     .05       01689.709    .045       01829.609      .1       0
 1843.57     .05       0  3166.7     .06       0  3206.7     .05       0
Bank Sta=1689.709,1829.609
XS Rating Curve= 0 ,0
Exp/Cntr(USF)=0,0
Exp/Cntr=0.3,0.1

Type RM Length L Ch R = 1 ,54105   ,225.3,215.1,207.7
BEGIN DESCRIPTION:
Structure XS 4
END DESCRIPTION:
XS GIS Cut Line= 3
2198195.81829707734474.8051099472197330.10294797734143.520535921
2196069.69921906733868.928717367
#Sta/Elev= 30
       0 1453.54    16.7 1454.76    60.5 1453.31   188.1 1453.18   267.4 1446.14
     308 1437.81   342.2 1434.02   350.4 1430.03   376.5 1413.38   389.4 1408.21
   402.2 1400.46  424.911392.971   432.2 1389.87   522.1 1389.84   530.7  1390.5
     535 1392.93   543.5  1397.9   556.4 1399.31   586.4 1406.78   813.4 1404.81
   916.2 1405.31     991 1407.28  1199.4 1407.12    1281 1405.77  1362.9 1406.96
  1538.9 1405.22  1661.7 1406.94  1895.1 1406.25  2065.4 1409.25  2216.9 1420.94
#Mann= 5 ,-1,0
       0     .05       0     250      .1       0  424.91    .045       0
     535    .025       0     560     .05       0
Bank Sta=424.91,535
XS Rating Curve= 0 ,0
Exp/Cntr(USF)=0,0
Exp/Cntr=0.3,0.1

Type RM Length L Ch R = 1 ,53890   ,43.3,43,43.1
BEGIN DESCRIPTION:
Structure XS 3
END DESCRIPTION:
XS GIS Cut Line= 4
2198324.77280678734228.0244612992197688.76893117734065.507500456
2197351.23370481734082.6967943912196104.28550213733842.028274976
#Sta/Elev= 30
       0 1433.38    78.5 1433.31   186.4 1428.17     233 1427.46   318.5 1429.28
     397 1425.74   405.2 1423.87   417.6 1417.35   442.4 1414.64   466.5 1399.32
   471.3 1394.37   475.4 1391.29   483.7 1389.84   578.6 1389.84   582.7 1390.31
  588.731394.413   595.1 1397.93   611.2 1399.53   644.7 1406.54   745.1 1407.02
   881.5 1404.37  1002.4 1404.61  1066.6 1407.03  1201.2 1405.83  1294.9 1407.53
  1584.2 1405.17  1864.6 1407.09  2007.8  1406.3  2138.2 1409.62  2264.4 1420.74
#Mann= 5 ,-1,0
       0     .05       0     370      .1       0     470     .05       0
   471.3    .045       0  588.73     .05       0
Bank Sta=471.3,588.73
XS Rating Curve= 0 ,0
Exp/Cntr(USF)=0,0
Exp/Cntr=0.3,0.1