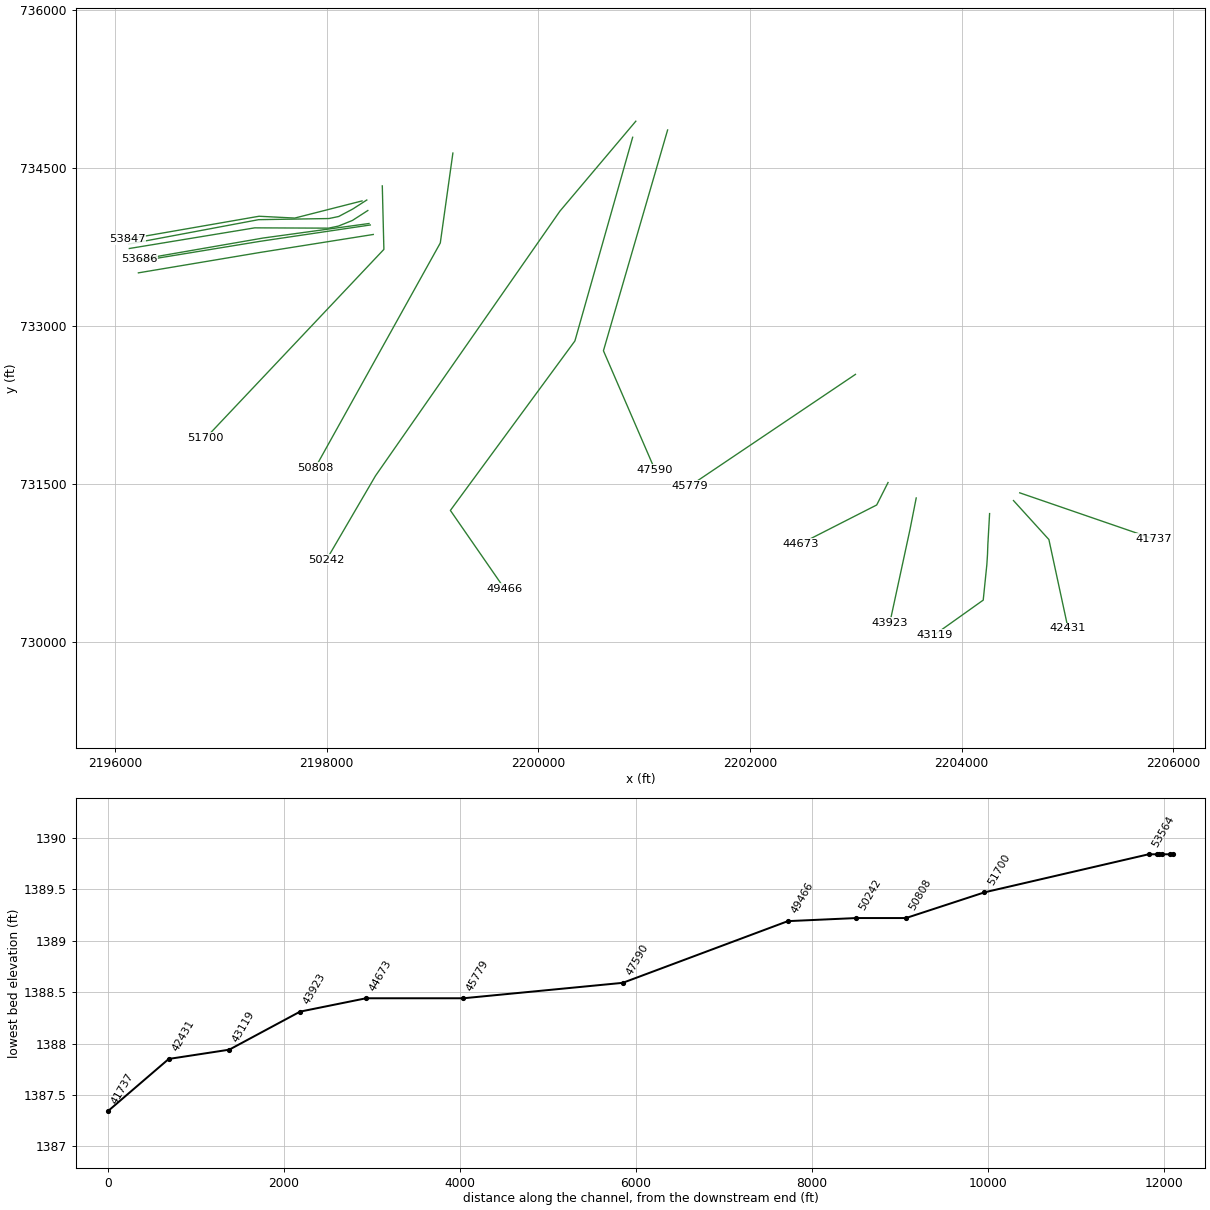
HEC-RAS study BUCKHANR_L.prj: BUCKHANR_L

--- BUCKHANR_L.g01 (geometry) --- (continued)

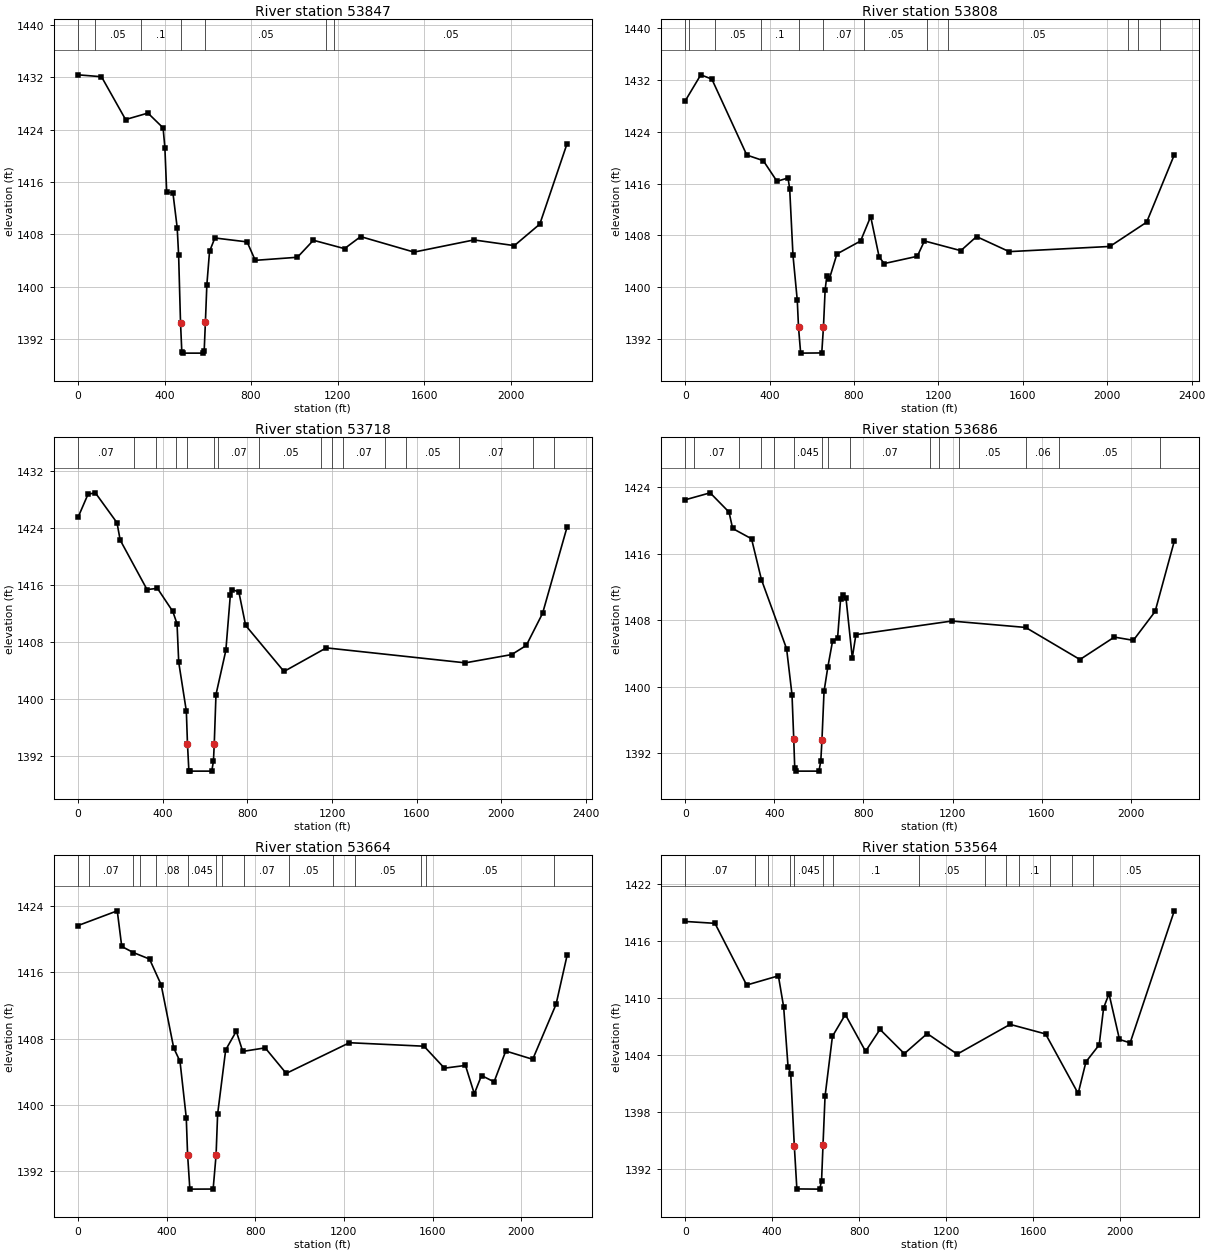
Type RM Length L Ch R = 1 ,53847   ,58.3,38.5,21.6
BEGIN DESCRIPTION:
Structure XS 2
END DESCRIPTION:
XS GIS Cut Line= 4
2198333.36745375734185.8325580032197697.36357814 734023.31559716
2197359.82835178734040.5048910952196111.97134282733822.813673267
#Sta/Elev= 30
       0  1432.4   108.6 1432.11     220 1425.56   323.3 1426.55   393.4 1424.29
   401.7 1421.26     410 1414.48   438.9 1414.34   458.6 1409.02   465.2 1404.83
  473.96 1394.51   480.1 1389.94   484.9 1389.84   579.2 1389.84   583.4 1390.21
     589 1394.56   595.7 1400.27   608.1 1405.39   632.8 1407.45   781.8 1406.85
   819.4 1404.03  1014.5  1404.5  1088.3  1407.1  1232.1 1405.82  1306.7 1407.66
  1553.6 1405.29  1830.5 1407.15  2017.3 1406.28    2135 1409.57  2261.1 1421.88
#Mann= 7 ,-1,0
       0     .07       0      80     .05       0     290      .1       0
  473.96    .045       0     589     .05       0 1144.41     .07       0
 1184.41     .05       0
Bank Sta=473.96,589
XS Rating Curve= 0 ,0
Exp/Cntr(USF)=0,0
Exp/Cntr=0.3,0.1

Type RM Length L Ch R = 1 ,53808   ,92.4,90.3,87.7
BEGIN DESCRIPTION:
Structure XS 3
END DESCRIPTION:
XS GIS Cut Line= 6
2198378.20881051734194.578326709 2198245.3074233734108.835496255
 2198112.4060361 734038.097661132198020.23249336734018.805524278
2197355.72555734734008.0876704712196127.34302418733776.698629167
#Sta/Elev= 30
       0 1428.76    73.8 1432.78   126.2 1432.12   291.8  1420.4   369.8 1419.54
   434.9 1416.35     487 1416.87     495 1415.21   510.6 1404.95     531 1397.98
  536.88 1393.81     547 1389.84     647 1389.87     655 1393.83     663 1399.61
     671 1401.76     683  1401.3   718.9 1405.14     831 1407.14   878.8 1410.91
     919 1404.67     943 1403.66  1099.6 1404.78  1133.5 1407.15  1305.9 1405.65
  1380.5 1407.82  1535.1  1405.5  2012.4  1406.3  2186.4 1410.04  2317.5 1420.44
#Mann= 12 ,-1,0
       0     .06       0      20     .07       0     140     .05       0
  358.71      .1       0  536.88    .045       0     655     .07       0
  848.78     .05       0  1147.5     .07       0  1247.5     .05       0
  2097.5     .07       0  2147.5     .06       0  2247.5     .05       0
Bank Sta=536.88,655
XS Rating Curve= 0 ,0
Exp/Cntr(USF)=0,0
Exp/Cntr=0.3,0.1

Type RM Length L Ch R = 1 ,53718   ,20.3,32.4,43
BEGIN DESCRIPTION:
Structure XS 2
END DESCRIPTION:
XS GIS Cut Line= 6
2198387.85487893734094.9022863062198242.09206716734000.585172807
2198109.19067996733946.9959037732198017.01713722733927.703766921
 2197318.6483301733930.4154428342196133.93776685733734.746842618
#Sta/Elev= 30
       0 1425.42    47.4 1428.69      82 1428.88   184.3 1424.68   199.2 1422.26
   326.2 1415.31   375.2 1415.48   447.9 1412.24   467.9 1410.51   475.9 1405.11
   511.9 1398.25  517.18 1393.67   523.9 1389.86   527.9 1389.84   631.9 1389.84
   639.9 1391.23  643.77 1393.69   651.9 1400.58   698.5 1406.77   719.9  1414.6
   727.9  1415.3   759.9 1414.99     792 1410.28   973.2 1403.82  1173.1 1407.13
  1829.8 1405.03  2048.8 1406.19  2117.8 1407.47  2194.8 1411.97  2310.6 1424.08
#Mann= 16 ,-1,0
       0     .07       0  263.62     .05       0  366.91      .1       0
  461.09    .025       0  517.18    .045       0  643.77     .08       0
  661.09     .07       0  856.92     .05       0 1149.82     .07       0
 1199.82     .06       0 1249.82     .07       0 1449.82     .06       0
 1549.82     .05       0 1799.82     .07       0 2149.82     .06       0
 2249.82     .05       0
Bank Sta=517.18,643.77
XS Rating Curve= 0 ,0
Exp/Cntr(USF)=0,0
Exp/Cntr=0.3,0.1

Type RM Length L Ch R = 1 ,53686   ,20.9,21.8,22.6
BEGIN DESCRIPTION:
Structure XS 4 AND 1
END DESCRIPTION:
XS GIS Cut Line= 3
2198398.96449813733971.6275965682197398.86012371733834.113245086
2196231.10187341733630.667656184
#Sta/Elev= 30
       0 1422.49   111.8 1423.33   196.6 1421.01   212.8 1419.04   297.6  1417.8
   342.1 1412.88     455 1404.56   479.3 1399.02  487.13 1393.65   491.4 1390.26
   495.4 1389.84   600.4 1389.84   608.5 1391.09   613.7 1393.62     623 1399.43
     640 1402.36     661 1405.45   683.9  1405.9   697.3 1410.53   709.4    1411
   721.7 1410.62   749.8 1403.47   765.9 1406.26  1195.9  1407.9  1527.9 1407.13
  1771.5 1403.27  1925.8 1405.97  2011.1 1405.58  2108.8 1409.05  2194.9 1417.52
#Mann= 15 ,-1,0
       0     .05       0      40     .07       0     240     .05       0
     340      .1       0     400     .08       0  487.13    .045       0
   613.7     .07       0     640      .1       0     740     .07       0
 1099.51     .05       0 1139.51      .1       0 1229.51     .05       0
 1529.51     .06       0 1679.51     .05       0 2129.51     .07       0
Bank Sta=487.13,613.7
XS Rating Curve= 0 ,0
Exp/Cntr(USF)=0,0
Exp/Cntr=0.3,0.1

Type RM Length L Ch R = 1 ,53664   ,98.4,99.5,99.9
BEGIN DESCRIPTION:
Structure XS 3
END DESCRIPTION:
XS GIS Cut Line= 3
2198411.43415731 733957.713757582197373.94590881733803.376662762
2196231.10187341733615.295974817
#Sta/Elev= 30
       0 1421.65   177.2 1423.43   197.4 1419.13     250 1418.39   322.8 1417.61
   375.3  1414.5     432 1406.87   460.3 1405.27   488.6 1398.46  494.54 1394.01
   504.8 1389.84   609.9 1389.85  623.16 1393.97   630.1  1398.9   666.5 1406.65
   714.4  1408.9   743.4 1406.46   844.7 1406.89   939.7 1403.81    1225 1407.51
  1561.5 1407.09  1653.6 1404.44  1748.5 1404.77  1788.5 1401.35  1820.9 1403.55
  1877.7 1402.79  1930.4 1406.51    2052 1405.51  2157.4 1412.15  2207.1 1418.05
#Mann= 15 ,-1,0
       0     .05       0      50     .07       0     250     .05       0
     280     .07       0     350     .08       0  494.54    .045       0
  623.16     .07       0     650      .1       0     750     .07       0
     950     .05       0 1148.91      .1       0 1248.91     .05       0
 1548.91     .06       0 1568.91     .05       0 2148.91     .07       0
Bank Sta=494.54,623.16
XS Rating Curve= 0 ,0
Exp/Cntr(USF)=0,0
Exp/Cntr=0.3,0.1

Type RM Length L Ch R = 1 ,53564   ,1836,1864.4,1872.2
BEGIN DESCRIPTION:
Structure XS 2
END DESCRIPTION:
XS GIS Cut Line= 3
 2198439.3005772733867.6837856032197376.08947957733698.341695456
2196219.57311238733503.851284908
#Sta/Elev= 30
       0 1418.08   136.8 1417.88   282.6 1411.37   428.5 1412.34   452.8 1409.05
   472.9 1402.77   485.2 1402.02   501.81394.389   513.5 1389.86   618.8 1389.84
   627.1 1390.74   633.81394.543   643.1 1399.63   677.1 1405.96   736.3 1408.26
   829.4 1404.38   895.9 1406.69  1007.7 1404.13    1113 1406.25  1250.9 1404.08
  1494.2 1407.22  1657.4 1406.21  1807.2 1399.93  1843.1 1403.27  1903.9 1405.06
  1924.3 1408.96  1949.1 1410.45  1997.3 1405.63  2046.3 1405.27  2249.4  1419.2
#Mann= 14 ,-1,0
       0     .07       0     320      .1       0     380     .08       0
     480      .1       0   501.8    .045       0   633.8     .07       0
     680      .1       0 1076.61     .05       0 1376.61      .1       0
 1476.61     .05       0 1536.61      .1       0 1676.61     .07       0
 1776.61      .1       0 1876.61     .05       0
Bank Sta=501.8,633.8
XS Rating Curve= 0 ,0
Exp/Cntr(USF)=0,0
Exp/Cntr=0.3,0.1

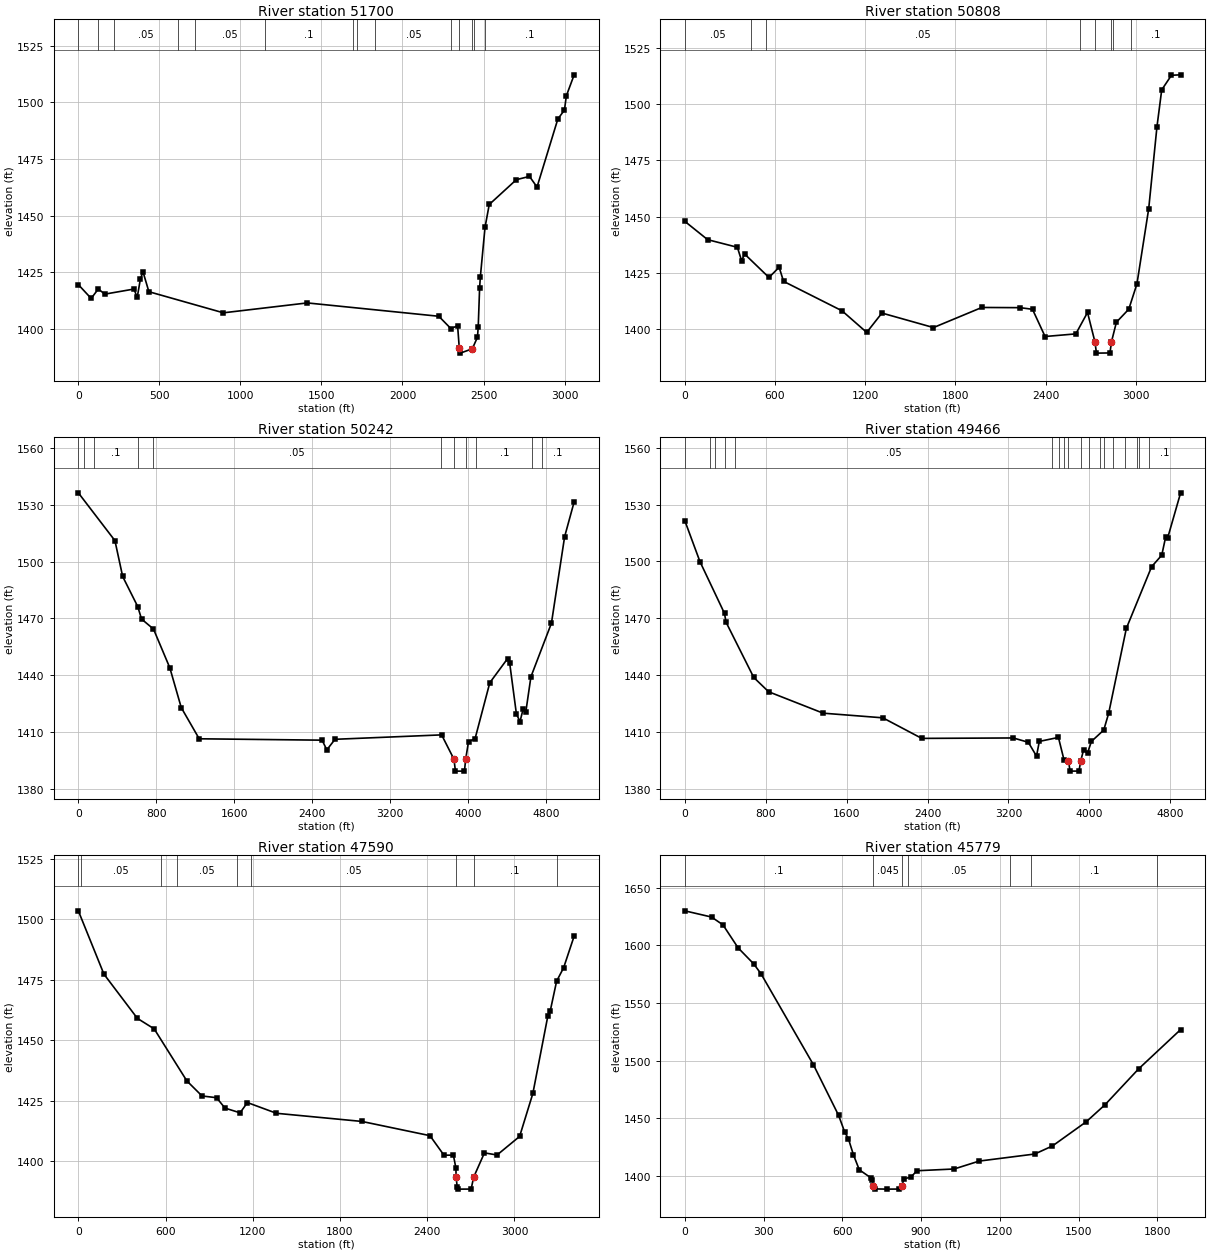
Type RM Length L Ch R = 1 ,51700   ,877.7,892.4,902.4
XS GIS Cut Line= 3
2198524.68012172734328.3332115272198539.73513542 733726.40665178
2196855.15100909731937.611559676
#Sta/Elev= 30
       0 1419.65    79.2 1413.57   123.2 1417.73   163.2 1415.46   343.3  1417.7
   363.3 1414.01   383.3 1422.27   399.3 1425.23   435.3 1416.53     895 1407.23
  1412.5 1411.59  2224.1 1405.71  2299.3 1400.24  2340.1 1401.57  2350.71391.512
  2356.6 1389.47  2430.7 1391.37  2462.7 1396.46  2467.4 1401.04  2475.9 1418.09
  2480.2 1422.83  2509.3 1444.89  2535.4 1454.96  2702.7 1465.89  2783.6 1467.33
  2830.2 1462.64  2958.6 1492.61  2999.4 1496.56  3011.1 1502.82  3059.3 1512.08
#Mann= 14 ,-1,0
       0     .05       0     120     .08       0     220     .05       0
  612.11     .08       0  722.11     .05       0 1152.11      .1       0
 1692.11     .05       0 1722.11      .1       0 1832.11     .05       0
 2302.11      .1       0  2350.7    .045       0  2430.7     .06       0
 2442.11     .07       0 2512.11      .1       0
Bank Sta=2350.7,2430.7
XS Rating Curve= 0 ,0
Exp/Cntr(USF)=0,0
Exp/Cntr=0.3,0.1

Type RM Length L Ch R = 1 ,50808   ,571.1,565.2,555.9
XS GIS Cut Line= 3
2199191.90987021734639.6657753192199072.87564292733787.048519357
2197890.83808351731655.505379452
#Sta/Elev= 30
       0  1447.9   151.9 1439.74   349.8 1436.34   377.6 1430.42   398.3 1433.32
   559.9  1422.9   627.6 1427.47   656.8 1421.18    1046 1408.06    1210 1398.45
  1311.3 1407.06  1654.3  1400.6  1975.8 1409.55  2231.5 1409.46  2312.9 1408.73
  2396.5 1396.62  2601.1 1397.79  2678.9 1407.33  2728.2 1394.22  2738.3 1389.22
  2828.2  1389.3 2838.26 1394.27    2871 1402.98  2953.3 1408.78  3007.7 1420.07
  3085.9 1453.54  3140.8 1490.02  3172.4 1506.44  3237.2 1512.94  3298.2 1513.13
#Mann= 8 ,-1,0
       0     .05       0     440     .06       0     540     .05       0
 2630.89      .1       0  2728.2    .045       0 2838.26      .1       0
 2850.89     .06       0 2970.89      .1       0
Bank Sta=2728.2,2838.26
XS Rating Curve= 0 ,0
Exp/Cntr(USF)=0,0
Exp/Cntr=0.3,0.1

Type RM Length L Ch R = 1 ,50242   ,779.9,776.4,773.1
XS GIS Cut Line= 4
2200920.81795387734941.6906154392200202.84299804 734088.16993238
  2198460.110801731579.0138589672197997.79894197730784.686051751
#Sta/Elev= 30
       0 1536.47   375.6 1511.18     455 1492.21     610 1476.26   648.8 1469.69
   771.5 1464.39   939.3 1443.86  1056.5 1422.82  1240.7 1406.33  2502.1  1405.6
  2550.7 1400.47  2634.6 1406.06    3729  1408.4    3856 1395.48  3870.6 1389.22
  3963.2 1389.22 3976.01 1395.56  4004.9 1404.82  4072.1 1406.36  4223.4 1435.98
  4405.7 1448.74    4427 1446.59  4496.7 1419.46  4533.5 1415.43  4565.9 1422.12
  4593.6 1420.71  4645.6 1439.14  4856.2  1467.5  4991.6 1513.28  5089.4 1531.71
#Mann= 11 ,-1,0
       0      .1       0      60     .05       0     160      .1       0
     610     .06       0     770     .05       0 3725.34      .1       0
    3856    .045       0 3976.01     .06       0 4085.34      .1       0
 4660.33     .05       0 4760.33      .1       0
Bank Sta=3856,3976.01
XS Rating Curve= 0 ,0
Exp/Cntr(USF)=0,0
Exp/Cntr=0.3,0.1

Type RM Length L Ch R = 1 ,49466   ,1782.8,1876.4,1944.7
XS GIS Cut Line= 4
2200890.96788521734789.2338507592200345.09346444732858.234766889
2199168.14158958731251.357922686 2199681.2067916  730507.7815554
#Sta/Elev= 30
       0 1521.58   149.7 1499.93   392.6 1472.53   407.4 1467.94   681.8 1438.69
   828.7 1431.14  1367.6 1419.82  1957.9 1417.36  2342.9 1406.49  3247.5 1406.72
  3395.9 1404.44  3477.2 1397.12  3504.9 1404.89  3693.8    1407  3748.3 1395.27
  3792.9 1394.69  3808.9 1389.19    3897 1389.22 3914.71 1394.66  3941.7 1400.27
  3981.3 1398.76  4020.2  1404.9  4142.1 1410.91  4190.7 1419.81  4365.3 1464.64
  4615.4 1497.25  4715.5 1503.32  4754.4 1513.08  4773.8 1512.43  4901.9 1536.27
#Mann= 18 ,-1,0
       0     .05       0     250      .1       0     300     .05       0
     400     .06       0     500     .05       0 3626.67      .1       0
 3696.67     .05       0 3746.67      .1       0  3792.9    .045       0
 3914.71    .025       0 3996.67     .07       0 4108.47     .06       0
 4148.47      .1       0 4228.47     .05       0 4348.47      .1       0
 4468.47     .07       0 4488.47     .06       0 4588.47      .1       0
Bank Sta=3792.9,3914.71
XS Rating Curve= 0 ,0
Exp/Cntr(USF)=0,0
Exp/Cntr=0.3,0.1

Type RM Length L Ch R = 1 ,47590   ,1907,1810.8,1695.2
XS GIS Cut Line= 3
2201221.26418617734858.330946177 2200614.7981215732765.164236447
2201102.58565615 731634.41291642
#Sta/Elev= 30
       0 1503.49     176 1477.36   406.4 1459.08   521.8 1454.75   746.6 1433.27
   850.8 1427.05   950.7 1426.34    1009 1422.04  1112.6  1420.1  1163.1 1424.33
    1363  1419.9  1950.2 1416.54  2418.8 1410.66  2515.1  1402.6    2580 1402.62
  2597.2 1397.29  2598.8 1393.56  2606.2 1389.42  2614.9 1388.59    2702 1388.61
  2719.4 1393.52  2793.5 1403.56  2880.3 1402.68  3035.5 1410.35  3126.6 1428.09
  3230.3 1460.27  3245.5 1461.97  3290.1 1474.47    3338 1479.95  3410.7 1493.06
#Mann= 9 ,-1,0
       0      .1       0      20     .05       0     570     .06       0
     680     .05       0    1090     .06       0    1190     .05       0
  2598.8    .045       0  2719.4      .1       0 3289.25     .06       0
Bank Sta=2598.8,2719.4
XS Rating Curve= 0 ,0
Exp/Cntr(USF)=0,0
Exp/Cntr=0.3,0.1

Type RM Length L Ch R = 1 ,45779   ,1114.1,1105.4,1095.6
XS GIS Cut Line= 2
2202996.55902617732541.214289656  2201431.710853731484.071816069
#Sta/Elev= 30
       0 1629.84   101.8 1624.45   145.3 1617.69   203.2 1597.68   262.5 1583.82
   290.1  1575.3   490.1 1496.25     586 1452.34   608.7 1438.13   623.2 1432.07
   642.5  1418.1   664.6 1405.23   710.1 1398.01   714.8    1396  718.36 1391.43
   726.3 1388.61   771.8 1388.44   815.6  1388.5   825.9 1391.48   835.6 1397.36
   861.7 1398.93   883.8 1404.38  1025.9 1405.91    1121 1412.76  1332.8 1418.89
  1400.4  1425.9  1529.2  1446.9  1600.7 1461.67  1728.6 1492.77  1888.5 1526.84
#Mann= 7 ,-1,0
       0      .1       0  718.36    .045       0   825.9      .1       0
     850     .05       0    1240     .06       0    1320      .1       0
    1800     .05       0
Bank Sta=718.36,825.9
XS Rating Curve= 0 ,0
Exp/Cntr(USF)=0,0
Exp/Cntr=0.3,0.1

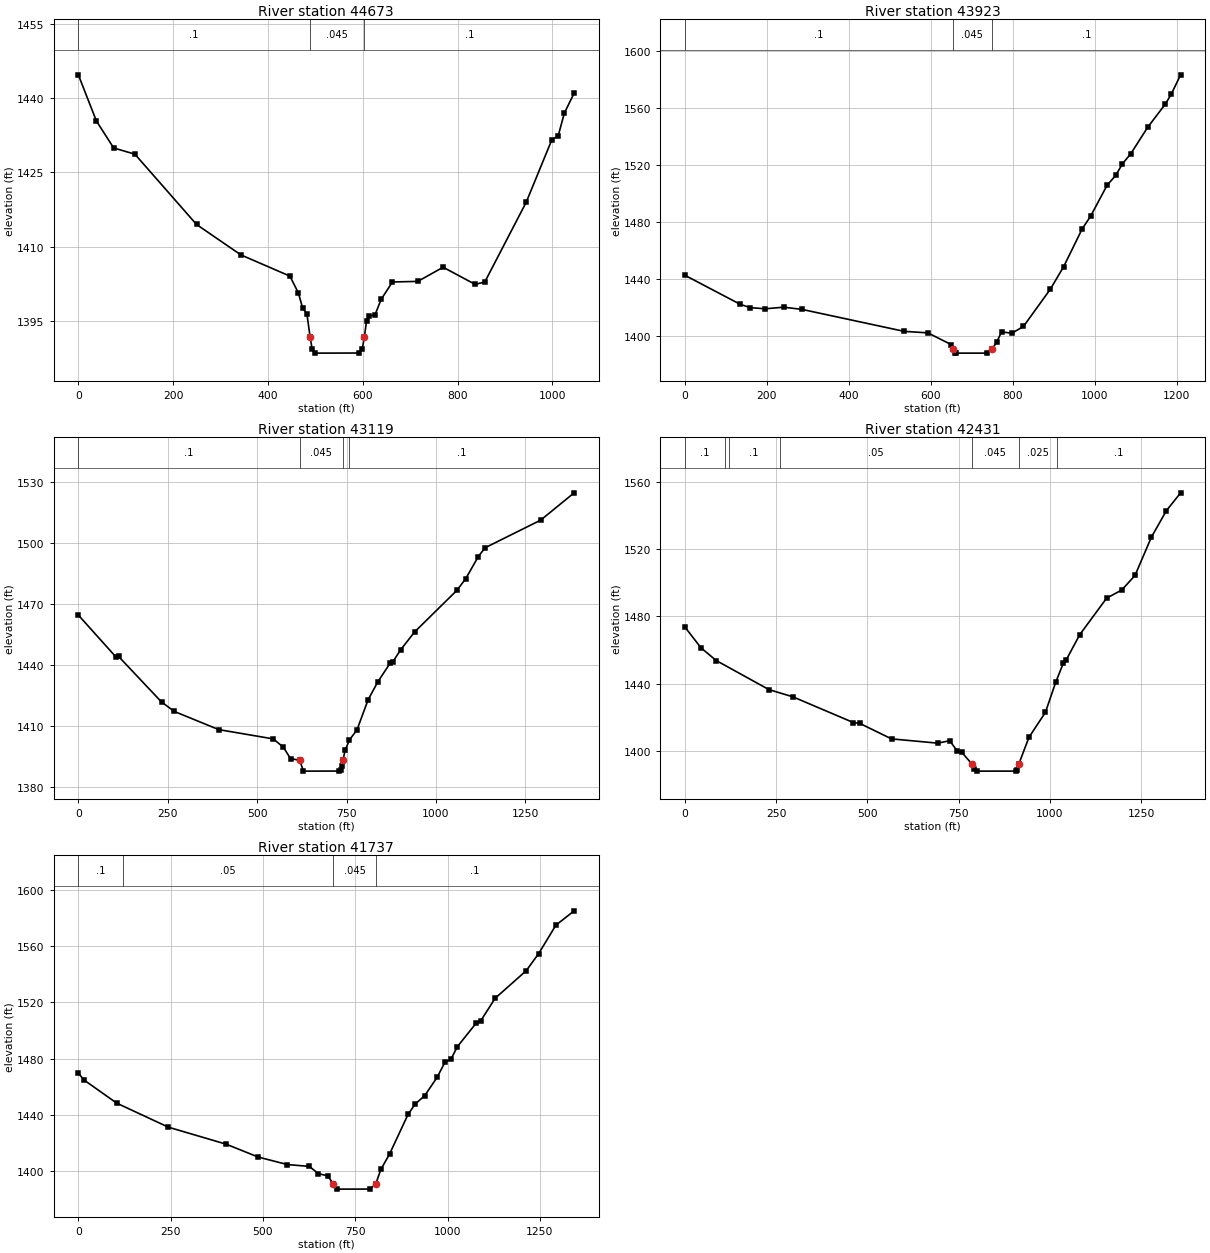
Type RM Length L Ch R = 1 ,44673   ,680.8,750,808.2
XS GIS Cut Line= 6
2203304.63658347731515.7157884442203197.40946084731302.982337087
  2202880.186342731140.8606140912202813.40235484731106.729448751
 2202652.0079926731024.2466740912202478.09200184730935.363977835
#Sta/Elev= 30
       0 1444.73      38 1435.42    74.5 1429.94   119.3 1428.68   249.4 1414.46
   342.9 1408.31   446.3 1404.02   464.2 1400.63   473.2 1397.55   482.2  1396.4
  488.921391.715   493.2 1389.27   500.2 1388.44   591.3 1388.46     599 1389.33
   603.5 1391.72     608 1394.96   612.5 1395.96   625.9 1396.19   638.8 1399.31
   662.6 1402.83   716.1 1402.95   769.6 1405.81   837.1 1402.35   857.5 1402.83
   944.9 1418.97   998.8 1431.57  1012.3 1432.38  1025.3 1436.99    1046 1441.04
#Mann= 3 ,-1,0
       0      .1       0  488.92    .045       0   603.5      .1       0
Bank Sta=488.92,603.5
XS Rating Curve= 0 ,0
Exp/Cntr(USF)=0,0
Exp/Cntr=0.3,0.1

Type RM Length L Ch R = 1 ,43923   ,795.8,804.7,812.7
XS GIS Cut Line= 6
2203571.01901107731369.5543180992203512.19295201731070.873221248
2203437.87125026730725.6580324172203416.82404825730627.898057342
2203382.62300117730469.037810758  2203321.783884730186.450449422
#Sta/Elev= 30
       0 1442.85   134.9 1422.51   159.4 1420.16   196.1 1419.34   241.2 1420.46
   285.4 1418.94   534.8 1403.55   592.6  1402.5   649.9 1394.26  653.02 1391.38
     658 1388.62   662.1 1388.31   735.8 1388.31   749.8 1391.34   760.4 1395.91
   772.6 1403.23   797.2 1402.21   825.8 1406.96   891.3 1433.02     924 1448.91
     969 1475.24   989.7 1484.22  1029.7 1505.76  1050.8 1512.73  1067.2 1520.77
  1087.7 1527.96  1128.6  1546.3  1172.2 1562.79  1185.9  1569.4  1209.1 1583.11
#Mann= 3 ,-1,0
       0      .1       0  653.02    .045       0   749.8      .1       0
Bank Sta=653.02,749.8
XS Rating Curve= 0 ,0
Exp/Cntr(USF)=0,0
Exp/Cntr=0.3,0.1

Type RM Length L Ch R = 1 ,43119   ,661,687.2,712
XS GIS Cut Line= 6
2204264.46964812 731221.395833832204248.05352447730927.362274424
2204244.59486996730830.3381902582204238.46955413730736.727157012
2204204.26489812730400.9650332642203745.32878017730073.401153951
#Sta/Elev= 30
       0 1464.62   104.4 1444.18   112.4 1444.31   232.6 1421.92   268.6 1417.25
   392.7 1408.34     545 1403.78   573.4 1399.71   593.5 1394.08   618.81393.304
   629.7 1387.94   730.2 1387.98   734.2 1388.46   738.2 1390.37  739.97 1393.29
   746.1 1398.08   758.3 1403.32     779 1408.09   810.6 1423.08   837.7 1431.83
   871.5 1440.86   880.2  1441.8   901.6 1447.62   940.9  1456.4  1058.9 1476.79
  1083.5 1482.52  1118.6 1493.35  1137.5 1497.68  1293.1 1511.27  1386.7 1524.68
#Mann= 4 ,-1,0
       0      .1       0   618.8    .045       0  739.97    .025       0
  757.89      .1       0
Bank Sta=618.8,739.97
XS Rating Curve= 0 ,0
Exp/Cntr(USF)=0,0
Exp/Cntr=0.3,0.1

Type RM Length L Ch R = 1 ,42431   ,600.8,694.3,771.6
XS GIS Cut Line= 3
2204490.44734208731344.8074789112204824.99600998730975.256544563
2205005.73556858730135.052586332
#Sta/Elev= 30
       0 1473.72    44.3 1461.27      86  1453.7   230.3  1436.4   296.3 1432.06
   461.5 1416.78   479.4 1416.25   566.1 1407.05   692.9  1404.5   725.6 1405.97
   745.3 1400.02   758.4 1399.11   786.51392.032   792.5 1389.04   799.2 1387.85
   905.7 1387.86   909.8 1388.76  914.61 1391.96   942.5 1407.97   987.5 1422.79
  1016.1 1440.91  1036.6 1452.12  1044.8 1454.14  1081.6 1469.08  1155.3 1490.84
  1196.6 1495.66    1233 1504.35    1278 1527.22  1318.9  1542.9  1357.9 1553.53
#Mann= 7 ,-1,0
       0      .1       0     110     .05       0     120      .1       0
     260     .05       0   786.5    .045       0  914.61    .025       0
 1018.49      .1       0
Bank Sta=786.5,914.61
XS Rating Curve= 0 ,0
Exp/Cntr(USF)=0,0
Exp/Cntr=0.3,0.1

Type RM Length L Ch R = 1 ,41737   ,1265.8,1310.1,1352.4
XS GIS Cut Line= 2
2204549.50933669731418.1646097782205818.97957648730979.923476345
#Sta/Elev= 30
       0 1469.69    15.5 1464.78   104.4 1448.32     244 1431.31   400.6 1419.23
   487.4 1410.09     566  1404.8   625.7 1403.46   650.3 1398.31   675.7 1396.76
  690.93 1390.88     701 1387.34   789.3 1387.38  805.431390.923   819.5 1401.37
   842.9  1412.2   893.1 1440.38   912.6 1447.81     938 1453.62   971.9 1466.75
     993 1477.39  1009.5 1479.71  1026.9 1488.55  1077.7 1505.22  1090.4 1507.03
    1129 1522.84  1213.1 1542.39  1246.9 1554.57  1293.5 1574.72    1343 1584.91
#Mann= 4 ,-1,0
       0      .1       0     120     .05       0  690.93    .045       0
  805.43      .1       0
Bank Sta=690.93,805.43
XS Rating Curve= 0 ,0
Exp/Cntr(USF)=0,0
Exp/Cntr=0.3,0.1