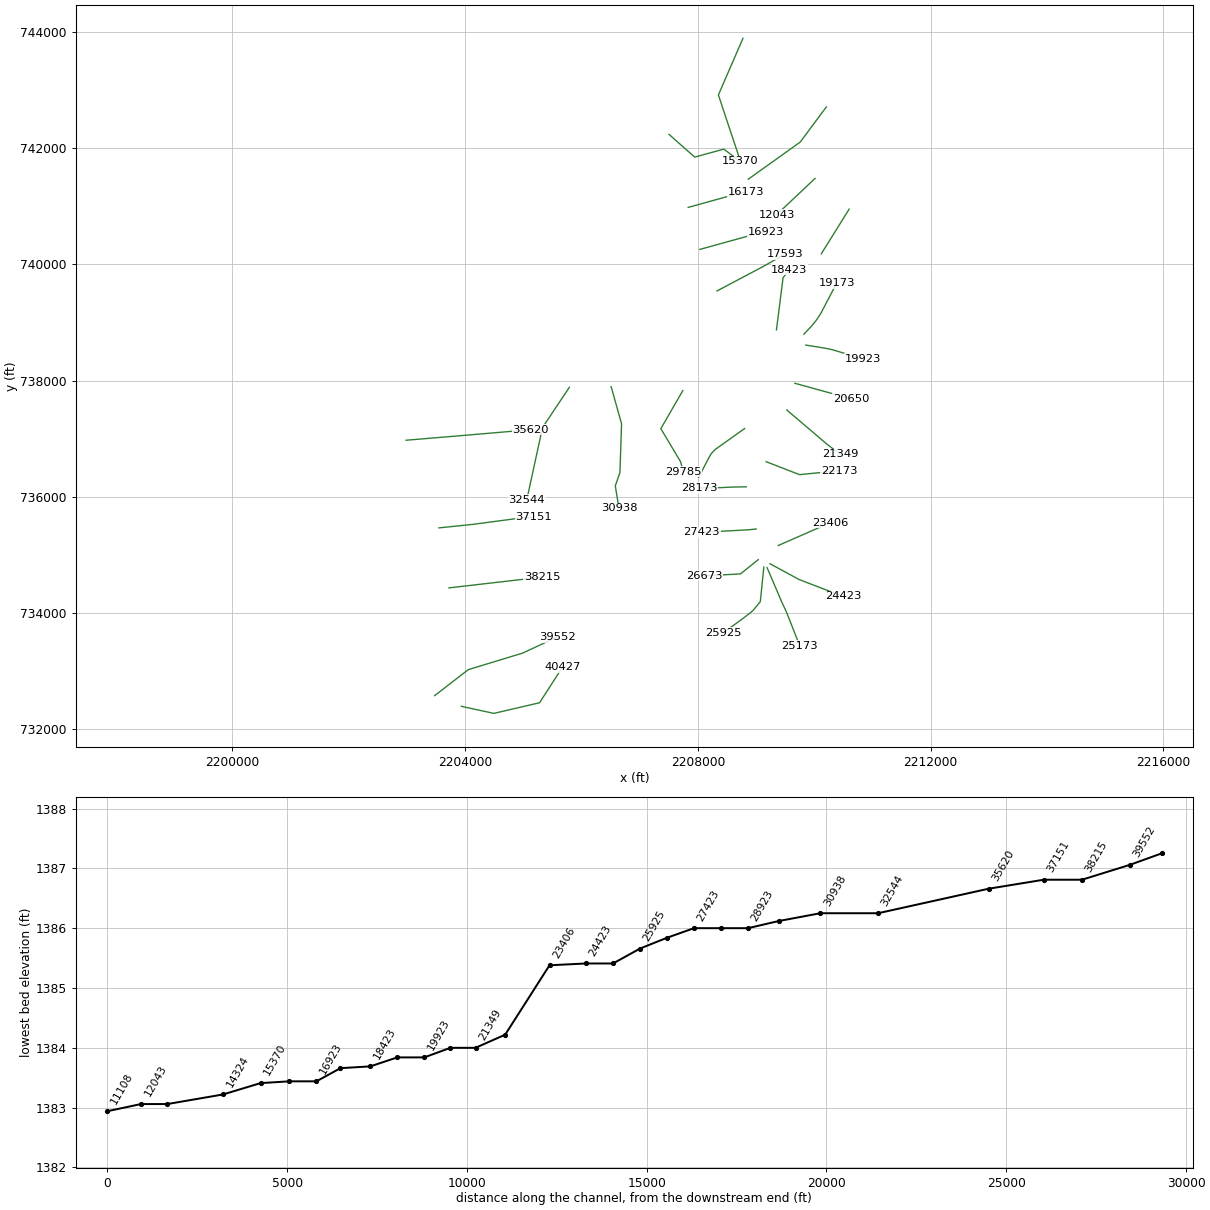
HEC-RAS study BUCKHANR_L.prj: BUCKHANR_L

--- BUCKHANR_L.g01 (geometry) --- (continued)

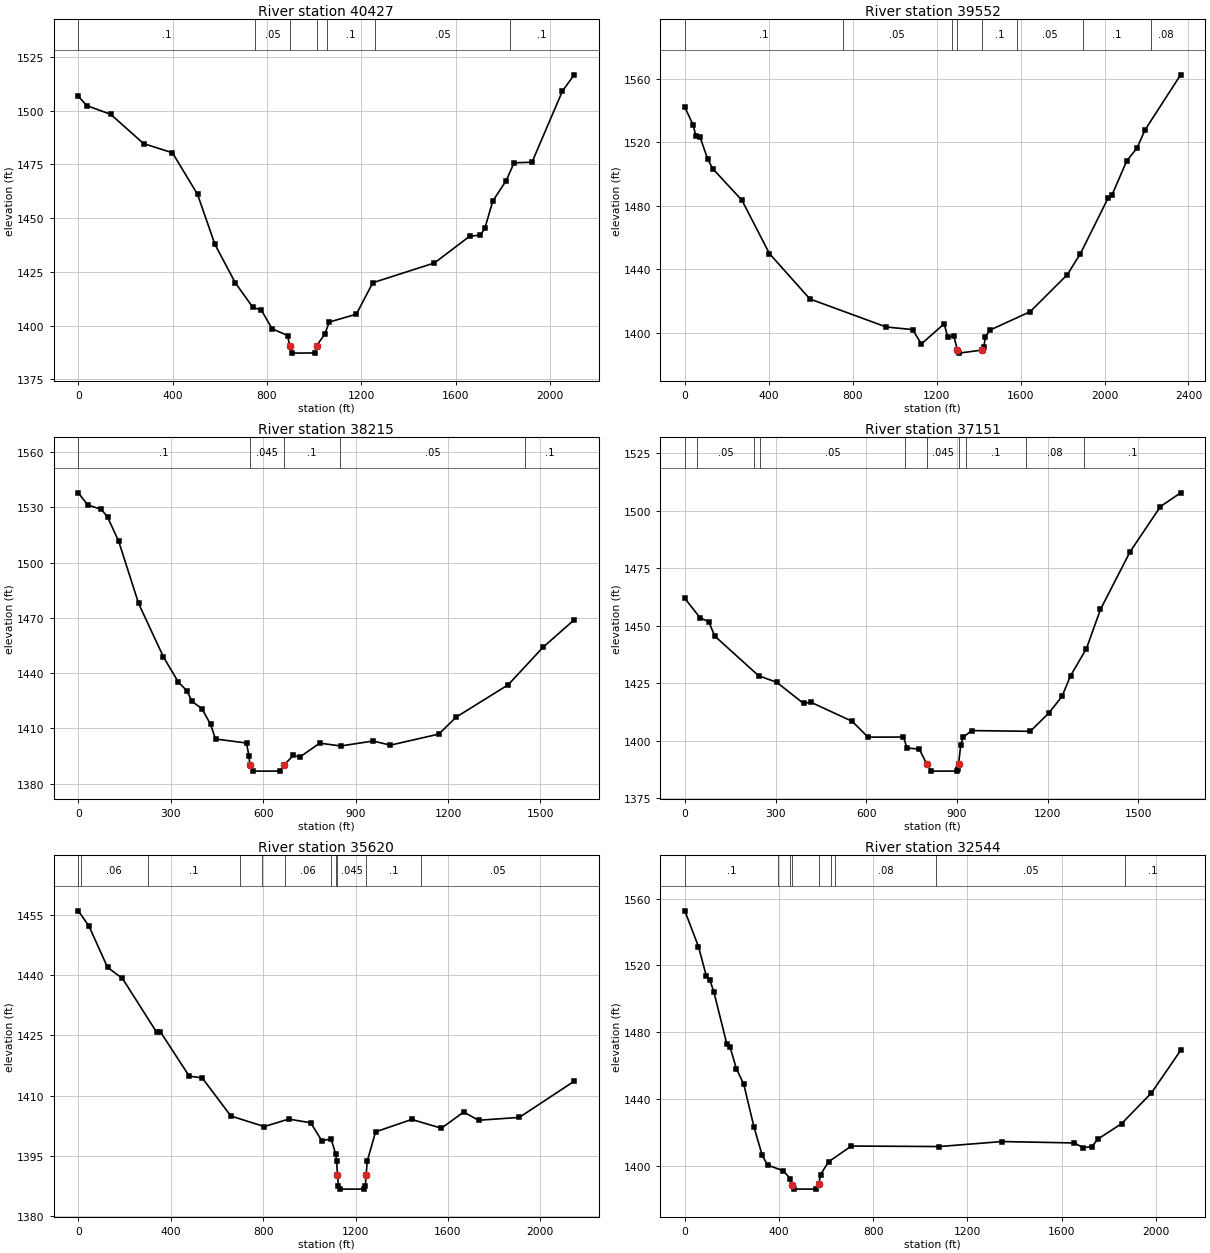
Type RM Length L Ch R = 1 ,40427   ,869.5,874.8,880.1
XS GIS Cut Line= 6
2203933.88307854732396.8346104332204493.86614349732275.726164237
2205008.20369749732395.6124074022205093.41940632732415.475556642
2205279.06798515732458.7481078962205670.28211473733067.567054277
#Sta/Elev= 30
       0 1506.78    35.1 1502.42   137.4 1498.32   276.5 1484.74   399.3 1480.43
   505.7 1461.07   579.3 1437.83   665.7 1419.95   739.6 1408.64   776.6 1407.18
   821.7 1398.61   887.4 1395.44  896.22 1390.73     908 1387.25  1002.4 1387.34
  1010.7  1390.7  1045.4 1396.11  1064.1  1401.7  1179.1 1405.35  1248.9    1420
  1510.4  1429.2  1659.6 1441.62  1705.4 1442.16  1724.4 1445.44  1757.7 1457.95
  1814.7 1467.54    1848 1475.77  1924.1 1476.07  2053.3 1509.18  2102.9 1516.71
#Mann= 7 ,-1,0
       0      .1       0   749.8     .05       0  896.22    .045       0
  1010.7     .07       0 1056.05      .1       0 1258.55     .05       0
 1829.18      .1       0
Bank Sta=896.22,1010.7
XS Rating Curve= 0 ,0
Exp/Cntr(USF)=0,0
Exp/Cntr=0.3,0.1

Type RM Length L Ch R = 1 ,39552   ,1351,1337.4,1323.6
XS GIS Cut Line= 4
2203475.05601128732580.5122992292204054.11687794733028.298691803
2204988.83163287733313.0104459952205580.93826082733589.556494831
#Sta/Elev= 30
       0 1542.27    40.3 1530.78    52.6 1524.15    72.6 1523.33   109.6 1509.28
   132.9 1503.45   272.2 1483.49   403.3 1449.84   596.1 1421.22   959.9 1403.55
  1085.4 1401.91  1127.2 1392.85  1235.9 1405.59  1252.7 1397.38  1281.9 1398.01
  1298.5 1388.99    1307 1387.06  1417.1    1389  1424.1 1390.62  1432.5 1397.13
  1453.4 1401.55  1645.7  1413.2  1823.2 1436.66    1885 1449.81  2017.4 1484.99
  2035.1 1486.61  2105.7 1508.33  2154.3 1516.33  2193.2  1527.9  2362.6 1562.62
#Mann= 8 ,-1,0
       0      .1       0     752     .05       0    1272     .06       0
  1298.5    .045       0  1417.1      .1       0    1582     .05       0
 1899.11      .1       0 2219.11     .08       0
Bank Sta=1298.5,1417.1
XS Rating Curve= 0 ,0
Exp/Cntr(USF)=0,0
Exp/Cntr=0.3,0.1

Type RM Length L Ch R = 1 ,38215   ,1064.3,1063.6,1065.9
XS GIS Cut Line= 2
2203721.81887725 734434.625146222205320.70264169734619.420757186
#Sta/Elev= 30
       0 1537.88    30.6 1531.28    74.9 1528.88      95 1524.68   131.2 1511.48
   195.6 1477.81   276.2 1448.81   324.5 1435.17   352.7 1430.37   368.8 1424.64
     401 1420.78   429.2 1412.17   445.3 1404.25     546 1402.06     554 1394.88
  556.82 1390.01   566.1 1386.81   654.1 1386.84   666.8 1389.92   697.4 1395.31
   719.1 1394.44   783.5    1402     852 1400.47   956.7 1403.15  1013.1 1400.92
  1170.1 1406.92  1226.5 1416.12  1395.6 1433.71  1508.3 1454.02  1609.5 1468.93
#Mann= 5 ,-1,0
       0      .1       0  556.82    .045       0   666.8      .1       0
     850     .05       0    1450      .1       0
Bank Sta=556.82,666.8
XS Rating Curve= 0 ,0
Exp/Cntr(USF)=0,0
Exp/Cntr=0.3,0.1

Type RM Length L Ch R = 1 ,37151   ,1534.5,1531,1526.4
XS GIS Cut Line= 6
2203549.58638023735466.6407155382204137.27502389735527.823305885
2204233.30468746735540.5926373112204840.46062539735621.326727803
2204936.49028897735634.0960592282205178.69181411735647.071098889
#Sta/Elev= 30
       0  1461.9    50.9 1453.41      79 1451.82    99.1 1445.51   243.9 1428.29
   304.2 1425.41   392.7 1416.23   416.3  1416.8   553.6 1408.45   605.9 1401.59
     723 1401.62     735 1396.86   775.4 1396.39   799.6 1390.06   815.7 1386.81
   900.5 1386.84   904.5 1387.81  905.42 1390.02   912.6 1398.21   920.6 1401.56
   948.9 1404.43  1142.6 1404.12  1203.1 1411.96  1247.5  1419.3  1275.7 1428.29
  1328.2 1440.08  1374.6  1457.1  1472.9 1482.25  1573.1 1501.84  1639.7 1507.79
#Mann= 10 ,-1,0
       0      .1       0      40     .05       0     230     .06       0
     250     .05       0  727.74     .06       0   799.6    .045       0
  905.42     .07       0  928.99      .1       0 1128.99     .08       0
 1320.24      .1       0
Bank Sta=799.6,905.42
XS Rating Curve= 0 ,0
Exp/Cntr(USF)=0,0
Exp/Cntr=0.3,0.1

Type RM Length L Ch R = 1 ,35620   ,3229.7,3076.7,2864.4
XS GIS Cut Line= 6
2202985.95590831736974.3281716122203758.94213042737038.945953504
 2203855.4658875737047.1883910752204285.15170792737083.881887243
2204465.74452259737099.3034443272205124.68970435737155.753760679
#Sta/Elev= 30
       0  1456.1    46.4 1452.24   126.3 1442.01   190.9 1439.23   339.4 1425.77
   355.5 1425.89   479.9 1414.86   536.1 1414.42   660.5  1404.9   804.8 1402.27
   910.7 1404.13  1005.7 1403.22  1053.9 1398.74  1094.1 1399.19  1114.1 1395.43
  1118.2 1393.67 1121.65 1390.25  1126.2 1387.41    1134 1386.66  1238.6 1386.67
  1242.6 1387.45  1245.9 1390.28  1250.6 1393.63  1286.8 1400.95  1443.3 1404.05
  1571.8 1401.86  1668.2  1405.9  1732.4 1403.84    1909 1404.56  2146.4 1413.58
#Mann= 11 ,-1,0
       0      .1       0      10     .06       0     300      .1       0
     700     .06       0  795.68     .07       0  892.56     .06       0
 1093.81     .07       0 1113.81      .1       0 1121.65    .045       0
  1245.9      .1       0 1485.06     .05       0
Bank Sta=1121.65,1245.9
XS Rating Curve= 0 ,0
Exp/Cntr(USF)=0,0
Exp/Cntr=0.3,0.1

Type RM Length L Ch R = 1 ,32544   ,1583.1,1605.6,1631.6
XS GIS Cut Line= 6
2205791.11891676737885.5552654922205630.78754451737645.033108732
2205395.05737294737291.4002858162205343.05813311737213.392895898
2205321.46366805737156.8892209052205058.63693275735948.204220898
#Sta/Elev= 30
       0 1552.66    58.1 1531.26    91.8 1513.49   106.2 1511.29   123.5 1504.14
   178.3  1473.1   192.8 1470.94   218.7 1458.36   250.5 1448.88   293.7 1423.44
   328.3 1406.56   351.2 1400.68   417.8 1397.23   447.5 1392.59   455.41389.008
   461.9 1386.29   558.1 1386.25  568.82 1389.09   576.4 1394.98   610.7 1402.61
   707.1 1412.02  1080.9 1411.71  1346.6  1414.7    1654 1413.86  1690.8 1411.04
  1727.6  1411.7  1755.5 1416.32  1854.5 1425.39  1981.4 1443.79  2105.2 1469.19
#Mann= 9 ,-1,0
       0      .1       0  396.56     .06       0  446.56      .1       0
   455.4    .045       0  568.82    .025       0  621.56      .1       0
  636.56     .08       0  1068.3     .05       0  1868.3      .1       0
Bank Sta=455.4,568.82
XS Rating Curve= 0 ,0
Exp/Cntr(USF)=0,0
Exp/Cntr=0.3,0.1

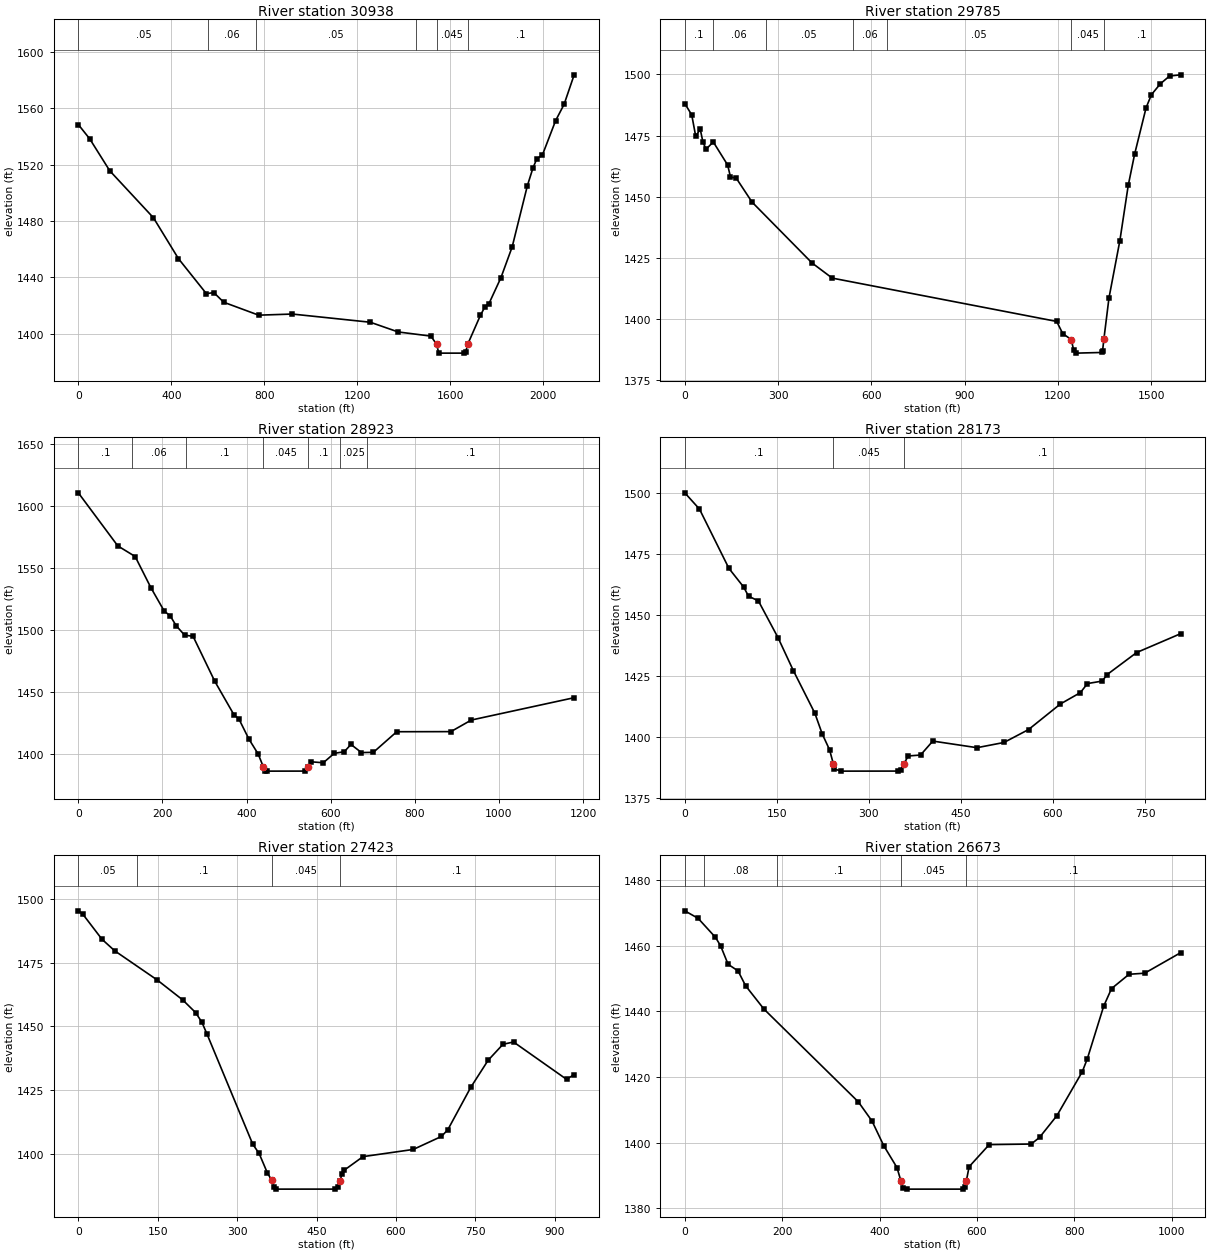
Type RM Length L Ch R = 1 ,30938   ,1082.5,1153.1,1230.5
XS GIS Cut Line= 5
2206508.62635923737896.5147272552206687.76530484737256.443736782
2206660.02467299736419.2085552772206580.11161091736189.134256917
2206642.30761754735806.428779754
#Sta/Elev= 30
       0 1548.57    49.2 1538.38   135.4 1515.72   323.3 1482.36   430.7 1453.37
   550.8 1428.52   583.3 1429.22   625.5  1422.4     776 1413.21     921    1414
  1256.3 1408.19  1376.3 1401.28  1517.2 1398.34  1541.6 1392.53  1551.1 1386.25
  1661.2 1386.25  1667.3 1387.34 1675.77  1392.6  1730.1 1413.07  1749.9 1419.21
  1766.9 1421.39  1818.4 1439.79  1866.8 1461.65  1932.3 1505.16  1956.6  1517.9
  1972.8 1524.17  1997.1 1527.02  2053.9 1551.39  2090.3 1562.93  2133.6 1583.89
#Mann= 6 ,-1,0
       0     .05       0     560     .06       0  764.67     .05       0
 1454.67      .1       0  1541.6    .045       0 1675.77      .1       0
Bank Sta=1541.6,1675.77
XS Rating Curve= 0 ,0
Exp/Cntr(USF)=0,0
Exp/Cntr=0.3,0.1

Type RM Length L Ch R = 1 ,29785   ,978.6,861.6,762.5
XS GIS Cut Line= 4
2207740.80784377737828.4906452882207362.48200508737173.341022201
2207700.82218602736607.3901740882207750.03530325736435.144263793
#Sta/Elev= 30
       0 1488.12    22.3 1483.49    35.1 1474.77    49.7 1477.64    58.5 1472.27
    68.5 1469.47    91.6 1472.43   137.8 1463.02     147 1458.09   165.5 1457.63
   216.3 1447.85   409.2 1422.98   474.3 1416.78  1196.4 1399.07  1215.8 1394.11
  1243.2 1391.67  1250.9 1387.42    1260 1386.12  1341.2 1386.39  1344.1 1387.13
 1348.09 1391.73  1364.6 1408.67  1399.6 1432.07  1426.5 1454.64  1447.3 1467.55
  1484.1 1486.45  1501.3 1491.77    1530 1496.21  1559.5 1499.37  1595.1 1499.86
#Mann= 7 ,-1,0
       0      .1       0      90     .06       0     260     .05       0
     540     .06       0     650     .05       0  1243.2    .045       0
 1348.09      .1       0
Bank Sta=1243.2,1348.09
XS Rating Curve= 0 ,0
Exp/Cntr(USF)=0,0
Exp/Cntr=0.3,0.1

Type RM Length L Ch R = 1 ,28923   ,796.5,750.2,711.7
XS GIS Cut Line= 6
2208802.14168967737175.6736756712208292.20963867736811.599600673
2208229.41678526736745.0403505862208173.40180543736647.728537336
2208102.47773467736509.3242865952208014.03171735 736337.83578442
#Sta/Elev= 30
       0 1610.29    93.8 1567.53   135.1 1558.97   172.4 1533.91   203.9 1515.16
   218.7 1510.98   232.6 1503.22   252.7 1495.55   272.7 1494.71   324.4 1458.39
   370.2  1431.3   381.7 1428.07   405.4 1411.91   427.6 1399.75   439.8 1389.49
   444.8 1386.35   449.7    1386   538.1 1386.03  546.11 1389.59   552.9 1393.53
   582.4 1392.74   608.2 1400.29   632.4 1401.67   648.1 1407.51   673.2 1400.95
   701.4 1401.15     757 1417.75   885.7 1417.83   934.2 1427.16  1178.8 1445.18
#Mann= 7 ,-1,0
       0      .1       0  128.44     .06       0  255.31      .1       0
   439.8    .045       0  546.11      .1       0  621.56    .025       0
  686.56      .1       0
Bank Sta=439.8,546.11
XS Rating Curve= 0 ,0
Exp/Cntr(USF)=0,0
Exp/Cntr=0.3,0.1

Type RM Length L Ch R = 1 ,28173   ,748.4,749.8,750.1
XS GIS Cut Line= 6
2208832.02548817736172.7885423452208650.65445983736170.036251262
 2208575.6359091736168.3262809222208400.87083867736159.248543173
2208122.89731325736155.9834578342208024.45689334736153.288581342
#Sta/Elev= 30
       0 1500.02    23.9 1493.36    71.9 1469.06    95.9 1461.42   103.9 1457.66
   119.9 1455.75   151.9 1440.68   176.8 1427.22   211.9 1409.73   223.9 1401.25
   235.9 1394.74242.00561388.995   243.9 1386.84   255.1    1386     348 1386.02
     352 1386.58  357.05 1388.99     364 1392.21   384.1 1392.59   404.1 1398.31
   476.1  1395.6   520.1 1397.74   560.1 1403.03   612.1 1413.53   644.6 1418.17
   656.1 1421.88   680.1 1422.89   688.1 1425.55   736.2 1434.58   807.9 1442.31
#Mann= 3 ,-1,0
       0      .1       0242.0056    .045       0  357.05      .1       0
Bank Sta=242.0056,357.05
XS Rating Curve= 0 ,0
Exp/Cntr(USF)=0,0
Exp/Cntr=0.3,0.1

Type RM Length L Ch R = 1 ,27423   ,750.1,750,750
XS GIS Cut Line= 6
2209000.62193576735447.5755780562208872.49555159735433.957670927
2208616.62893733735419.9422790112208441.89109784735410.371103927
2208164.18233567735395.1591920852208065.89217792735389.775344595
#Sta/Elev= 30
       0 1495.42     8.5 1494.09    44.7 1484.23    68.8 1479.69   148.9 1468.25
   197.3 1460.37   221.6  1455.4   233.3 1451.66   242.8 1447.11   329.5 1403.66
   341.5 1400.04   357.2 1392.35   365.4 1389.49   369.5 1386.97   373.5    1386
   485.7 1386.01   489.7 1386.77494.74031389.361   497.7 1391.87   501.7 1393.35
   537.8 1398.78   632.7  1401.6     686 1406.72     698 1409.35   741.3    1426
   774.1 1436.64   802.2 1442.94   822.2 1443.85   922.4 1429.16   936.7 1431.06
#Mann= 4 ,-1,0
       0     .05       0     110      .1       0   365.4    .045       0
494.7403      .1       0
Bank Sta=365.4,494.7403
XS Rating Curve= 0 ,0
Exp/Cntr(USF)=0,0
Exp/Cntr=0.3,0.1

Type RM Length L Ch R = 1 ,26673   ,697,748.8,794.5
XS GIS Cut Line= 6
 2209037.4785206734920.3938105512208732.11361451734675.065487921
2208482.47894317734661.5484545832208301.49439701734651.748605415
2208204.76099467734646.5104269242208106.46722801734641.188259095
#Sta/Elev= 30
       0 1470.58    27.3  1468.3      63  1462.5    73.5 1459.94    88.9 1454.31
   109.4 1452.27   124.8 1447.78   162.5 1440.67   356.4 1412.41   384.5 1406.57
   408.6 1399.06   435.7 1392.42443.7585 1388.39   447.7 1386.27   455.7 1385.84
   571.9 1385.84   575.9 1386.35  578.031388.196   583.9 1392.66   625.2 1399.39
   711.5 1399.57   728.5 1401.58   764.2 1408.21   816.3 1421.58   826.7 1425.54
   860.3 1441.56   876.4  1446.9   912.4 1451.26   944.5 1451.59  1018.3 1457.83
#Mann= 5 ,-1,0
       0     .05       0      40     .08       0     190      .1       0
443.7585    .045       0  578.03      .1       0
Bank Sta=443.7585,578.03
XS Rating Curve= 0 ,0
Exp/Cntr(USF)=0,0
Exp/Cntr=0.3,0.1

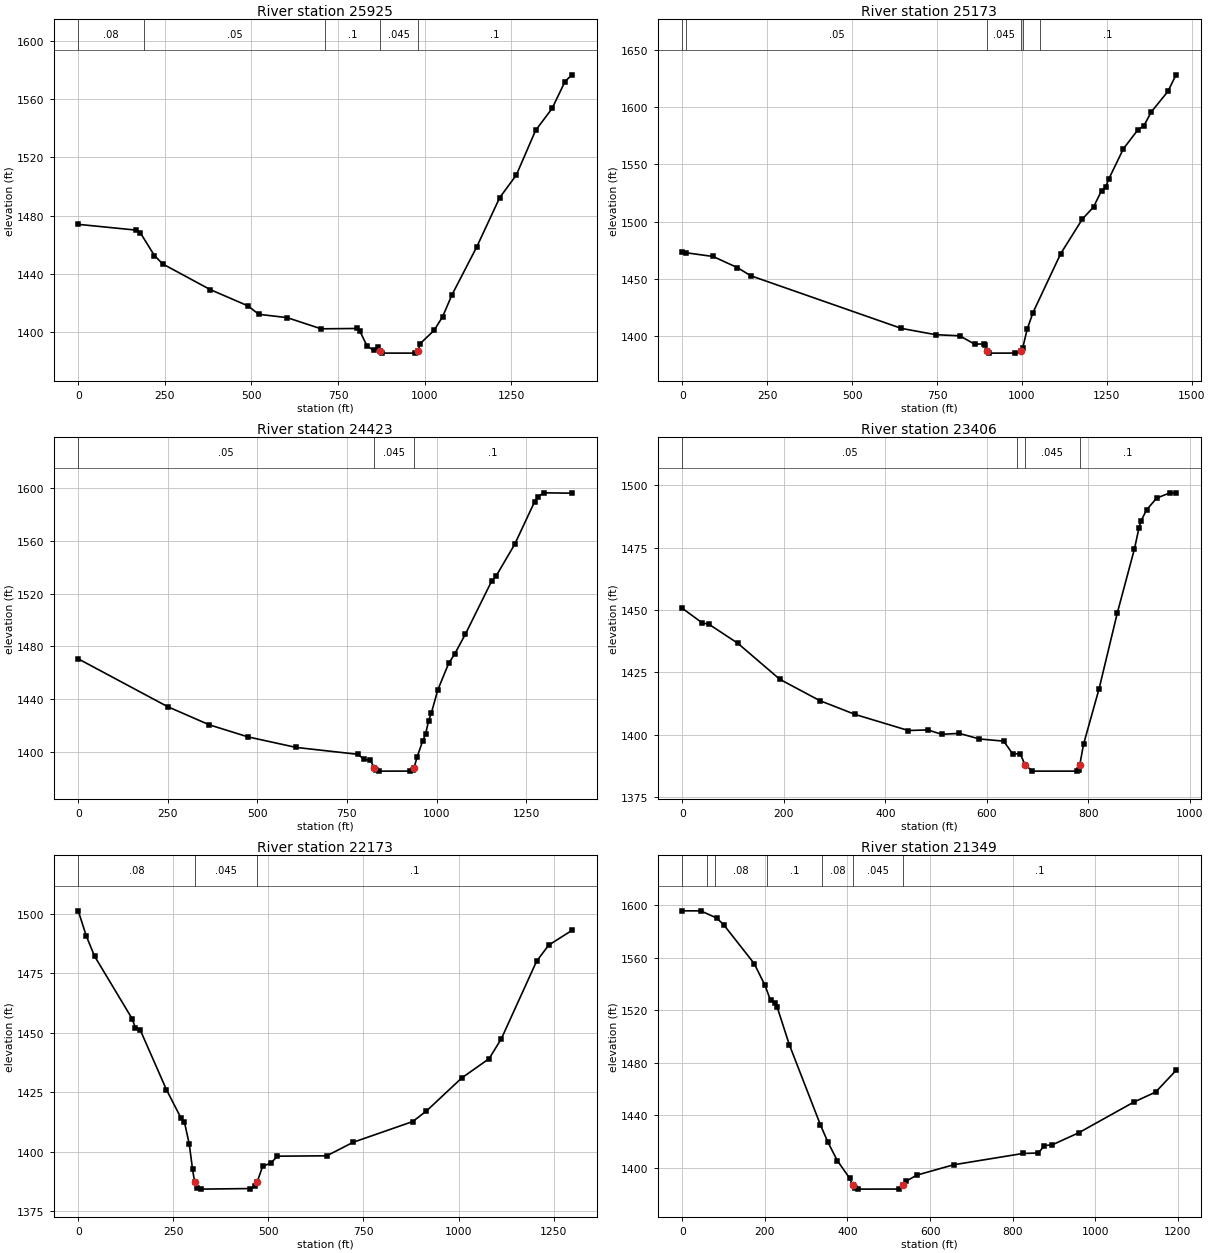
Type RM Length L Ch R = 1 ,25925   ,651.9,751.2,840.8
XS GIS Cut Line= 6
2209132.51406009 734791.853677372209071.91313176734197.774775833
2208943.87172118734042.2996930932208885.05490968733993.844081342
2208806.03111759733932.5043089992208442.97508517733666.447098345
#Sta/Elev= 30
       0 1474.09   167.5 1470.11   179.6 1468.16   219.8 1452.69   243.9 1446.88
   380.6 1429.33   489.2 1418.18   521.4 1412.31   603.1 1410.03     701 1402.35
   804.8 1402.59   813.4 1400.52   833.3 1390.66   853.2 1387.51   864.5 1389.77
  870.16 1387.34   875.9 1385.69   972.8 1385.66   980.4 1387.32   987.1 1392.22
  1027.2 1401.29  1051.7 1410.68  1078.6 1425.63  1150.2 1458.57  1216.3 1492.35
  1264.6 1508.03  1320.1  1538.6  1367.7 1553.65  1404.9 1572.12  1424.9 1576.75
#Mann= 5 ,-1,0
       0     .08       0     190     .05       0  713.03      .1       0
  870.16    .045       0   980.4      .1       0
Bank Sta=870.16,980.4
XS Rating Curve= 0 ,0
Exp/Cntr(USF)=0,0
Exp/Cntr=0.3,0.1

Type RM Length L Ch R = 1 ,25173   ,688.7,750,808.1
XS GIS Cut Line= 6
2209188.67711187734782.4194157782209442.09185334734188.360424593
2209482.32405634734103.4393345862209518.68651642734023.714100346
2209547.30817834733954.3779529182209748.89570168 733440.97379601
#Sta/Elev= 30
       0 1473.21      10 1472.98    90.5  1469.7   162.3 1459.96   201.4 1452.91
     645 1406.99   745.9  1401.5     817 1400.51   860.5 1393.28   888.7 1393.42
   891.8 1392.45   897.9 1387.42   903.7 1385.41   981.2 1385.44   998.3 1387.46
  1002.6  1390.1  1015.5 1406.19  1032.7 1420.76  1114.3 1472.16  1178.4 1502.42
  1211.3 1512.92  1234.6  1527.2  1246.6  1530.2  1256.1 1537.39    1299 1563.64
  1342.2  1580.4  1359.3 1583.62  1380.7  1595.6  1430.2 1613.72    1454 1628.13
#Mann= 6 ,-1,0
       0     .08       0      10     .05       0   897.9    .045       0
   998.3      .1       0 1002.46    .025       0 1052.46      .1       0
Bank Sta=897.9,998.3
XS Rating Curve= 0 ,0
Exp/Cntr(USF)=0,0
Exp/Cntr=0.3,0.1

Type RM Length L Ch R = 1 ,24423   ,958,1016.9,1074.7
XS GIS Cut Line= 6
2209238.54585233734849.8520163522209739.50792517734577.966600761
2209978.62457292734485.8404726682210071.93836267734449.888444841
2210141.92378701734422.9249160892210493.30858292734287.543953255
#Sta/Elev= 30
       0 1470.57   249.5 1434.31   365.9 1420.52   473.7 1411.38   608.2 1403.38
   780.7 1398.15   797.9 1394.31   815.6 1393.55  826.01 1387.99   832.2 1385.93
   840.3 1385.41   926.5 1385.43   935.1 1386.55  937.23 1387.99   945.5 1395.86
     961 1408.12   969.4 1413.45   977.9  1423.7   985.8 1429.75  1003.6 1447.08
  1033.7 1467.04  1050.8 1474.33  1080.8 1489.43  1153.7 1529.46  1166.5 1533.46
    1218 1557.37  1273.5 1589.58  1282.8 1593.49  1299.4 1596.46  1377.8 1596.19
#Mann= 3 ,-1,0
       0     .05       0  826.01    .045       0  937.23      .1       0
Bank Sta=826.01,937.23
XS Rating Curve= 0 ,0
Exp/Cntr(USF)=0,0
Exp/Cntr=0.3,0.1

Type RM Length L Ch R = 1 ,23406   ,1322.9,1233,1156.2
XS GIS Cut Line= 2
2209380.38462341735163.5921582882210271.16472803735554.369633215
#Sta/Elev= 30
       0 1450.67    39.1 1444.86    52.7 1444.25     109 1436.71     192 1422.22
   270.6 1413.68   340.5 1408.11   445.3 1401.67   483.8 1401.91   510.8 1400.15
   545.8 1400.52   585.1 1398.29   633.1 1397.41   650.6 1392.37   665.9 1392.29
   675.1 1387.91   689.9 1385.38   777.3 1385.38   781.6 1385.96  783.08  1387.9
   790.4 1396.11     821 1418.36   857.2 1448.98   890.8 1474.55   899.7 1482.96
   903.9 1485.82   914.9 1490.24   934.5 1494.88   960.7 1497.01   972.7 1496.87
#Mann= 4 ,-1,0
       0     .05       0     660      .1       0   675.1    .045       0
  783.08      .1       0
Bank Sta=675.1,783.08
XS Rating Curve= 0 ,0
Exp/Cntr(USF)=0,0
Exp/Cntr=0.3,0.1

Type RM Length L Ch R = 1 ,22173   ,851.4,824.9,794.5
XS GIS Cut Line= 6
2209172.17802309736605.6718629152209262.72607034736570.259860262
2209350.39420208736536.1286949222209595.61976151736440.915958837
2209746.51480092736382.1293310082210424.69806834736450.742716509
#Sta/Elev= 30
       0 1501.33    21.5 1490.62    42.9 1482.26   141.7 1455.93   150.3 1452.09
   163.2 1451.13   231.8 1426.11   270.5 1414.05   279.1 1412.51   291.9 1403.21
   300.5 1392.64306.22111387.089   312.4 1384.76   321.7 1384.22   450.7 1384.46
   463.9 1385.37470.02111387.065     485 1393.84   506.5 1395.17   523.6 1398.08
   653.5 1398.24   722.5 1403.91   879.3 1412.65   915.5 1417.09    1008 1430.96
  1080.3 1439.12  1112.5 1447.51  1205.2 1480.14  1237.1 1486.91    1298 1493.09
#Mann= 3 ,-1,0
       0     .08       0306.2211    .045       0470.0211      .1       0
Bank Sta=306.2211,470.0211
XS Rating Curve= 0 ,0
Exp/Cntr(USF)=0,0
Exp/Cntr=0.3,0.1

Type RM Length L Ch R = 1 ,21349   ,662.5,698.2,732.9
XS GIS Cut Line= 6
 2209527.9110804737494.0376267452209676.56334216737367.351200329
 2209747.9165459737306.5419387392210142.73760665736970.062952908
2210216.46941457736907.2264644082210448.24845696736731.335005598
#Sta/Elev= 30
       0 1595.65    44.5 1595.62    83.1 1590.19   100.1 1585.09     174 1555.55
   200.1 1539.02   213.6 1527.55     225 1525.31   229.5  1522.6     259 1493.93
   334.3 1432.96   352.5 1419.74   375.3 1405.71     405 1392.38  412.98 1386.94
   417.9 1384.56     426    1384   525.7 1384.06   534.2  1387.1   541.7 1389.99
   567.9 1394.64   657.3 1402.53   825.5 1411.15   862.3 1411.47     877 1417.16
   895.5 1417.63   959.6 1426.78  1093.3 1450.17  1146.3 1457.81  1195.7 1474.27
#Mann= 7 ,-1,0
       0     .08       0      60      .1       0      80     .08       0
  205.31      .1       0  339.06     .08       0  412.98    .045       0
   534.2      .1       0
Bank Sta=412.98,534.2
XS Rating Curve= 0 ,0
Exp/Cntr(USF)=0,0
Exp/Cntr=0.3,0.1

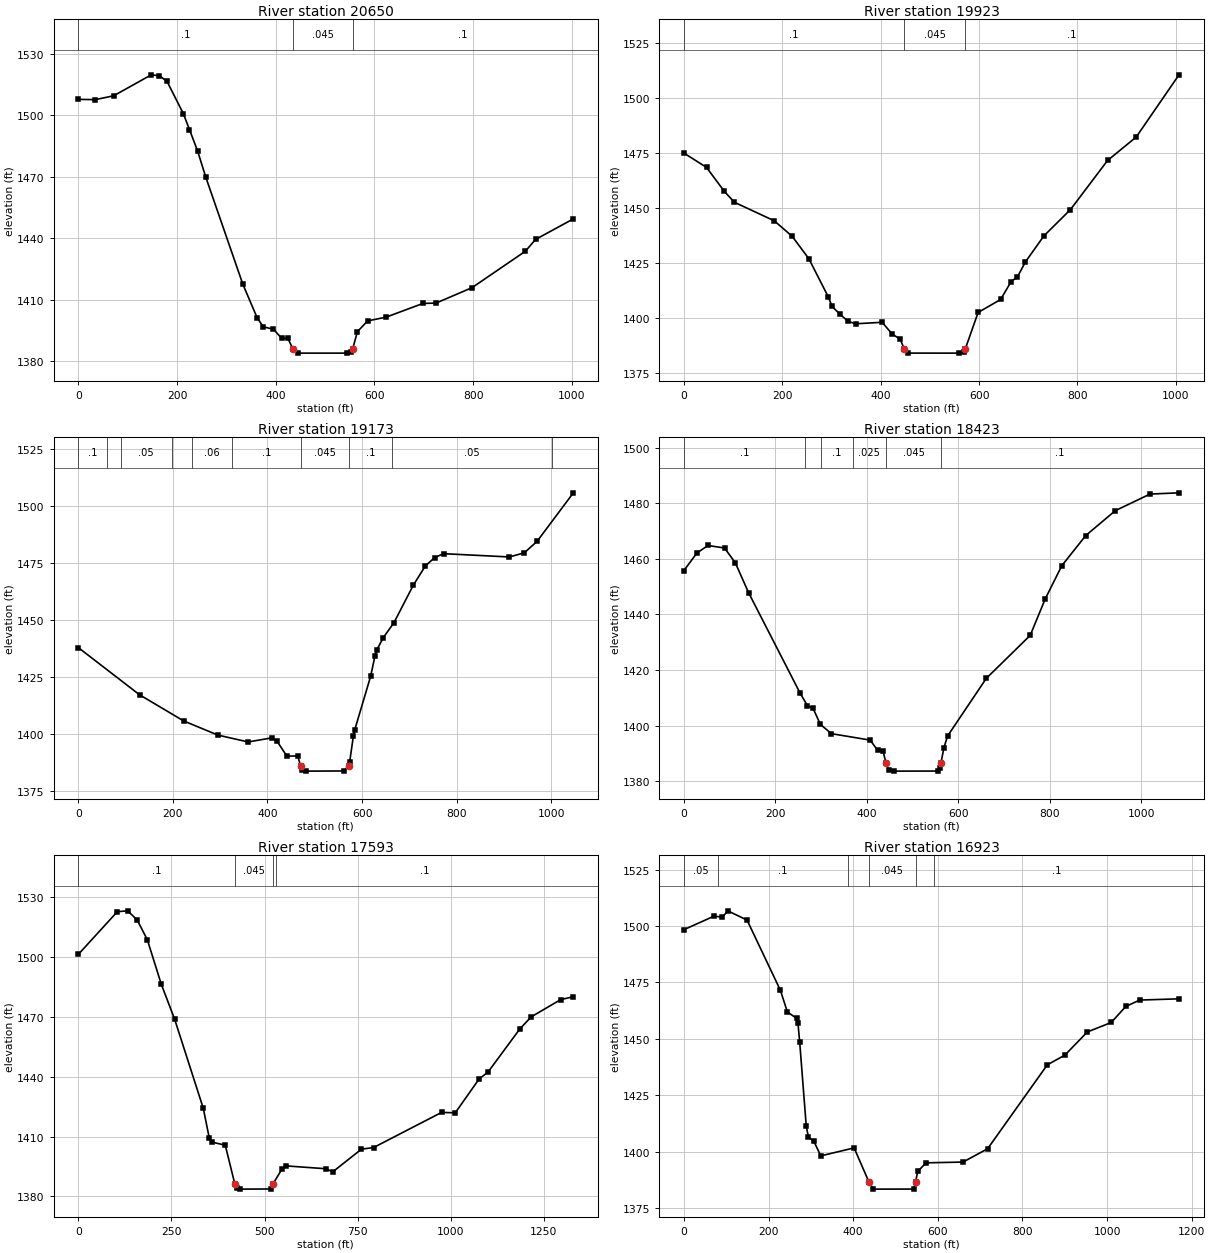
Type RM Length L Ch R = 1 ,20650   ,726.5,727,725.4
XS GIS Cut Line= 6
2209666.99102425737953.8079990242209945.66008634737876.990895444
2210102.31692526737833.8075828642210198.72126001737807.232832858
2210539.14905684737713.3918131972210634.04716101737687.232744777
#Sta/Elev= 30
       0  1507.7    34.4 1507.56    71.8 1509.45   147.8 1519.66   164.1  1519.2
   179.6 1516.54   212.8 1500.76   225.3 1492.96   241.9  1482.4   258.5 1469.65
   333.2 1417.72   362.2 1401.33   374.7 1396.82   395.4 1395.66     412 1391.23
   424.7 1391.14   435.31385.874   445.2    1384   544.8    1384   553.1 1384.46
   555.91385.989   565.5 1394.46   586.3 1399.72   623.6 1401.53   698.3 1408.22
   724.9  1408.4   797.9 1415.93   905.8 1433.66   926.5 1439.42  1003.1 1449.44
#Mann= 3 ,-1,0
       0      .1       0   435.3    .045       0   555.9      .1       0
Bank Sta=435.3,555.9
XS Rating Curve= 0 ,0
Exp/Cntr(USF)=0,0
Exp/Cntr=0.3,0.1

Type RM Length L Ch R = 1 ,19923   ,652.5,750,855.7
XS GIS Cut Line= 6
2209854.86432175738611.1252010912210049.38296159738579.954331666
2210142.57896942   738564.4123682210229.27400601738548.939958006
2210302.96611585738533.6079676752210831.51361518738375.941288263
#Sta/Elev= 30
       0 1474.93    45.9 1468.42    82.3 1457.45   102.6 1452.53   183.6  1444.1
   220.1 1437.02     254 1426.81   293.1 1409.61   301.2  1405.1   317.5 1401.49
   333.7 1398.33   348.8  1397.2   402.9 1397.88   423.4 1392.54   439.7 1390.16
   447.9 1385.71     456 1383.85     559 1383.84   568.7 1384.36   571.9 1385.72
     598 1402.36   643.9 1408.29   665.1 1416.42     678 1418.57   693.9 1425.28
   731.6 1437.18   785.8 1449.22   861.2 1471.57   919.4 1482.24  1006.4 1510.57
#Mann= 3 ,-1,0
       0      .1       0   447.9    .045       0   571.9      .1       0
Bank Sta=447.9,571.9
XS Rating Curve= 0 ,0
Exp/Cntr(USF)=0,0
Exp/Cntr=0.3,0.1

Type RM Length L Ch R = 1 ,19173   ,722.9,750,776.2
XS GIS Cut Line= 6
2209820.73709342738797.6103924212209963.63707009 738950.66126743
2210024.08609617739024.8097411692210074.32221617739097.309268087
2210114.26144075739161.047985762 2210382.5352126739673.235597338
#Sta/Elev= 30
       0 1438.03   129.5 1417.33   222.9 1405.84   295.2 1399.64     359 1396.64
     409 1398.42   420.6 1396.85   440.9 1390.41   463.9 1390.51     470  1386.1
   473.1 1384.54   482.2 1383.84   561.8 1383.91  571.65 1386.16   573.7 1387.79
   581.6 1399.26   584.4  1401.9   618.1 1425.46     627 1434.15   631.3 1437.09
   644.8 1442.39   667.4 1448.96   708.1 1465.31   733.6 1473.79   753.3 1477.49
   772.2 1479.22   911.4 1477.78     943  1479.6     970 1484.64  1046.7 1505.91
#Mann= 10 ,-1,0
       0      .1       0      60     .06       0      90     .05       0
  197.55     .07       0  239.39     .06       0  325.06      .1       0
     470    .045       0  571.65      .1       0  663.48     .05       0
 1001.61     .06       0
Bank Sta=470,571.65
XS Rating Curve= 0 ,0
Exp/Cntr(USF)=0,0
Exp/Cntr=0.3,0.1

Type RM Length L Ch R = 1 ,18423   ,898.3,830.5,754.1
XS GIS Cut Line= 6
2209349.35155326 738873.054795342209396.81176017739246.614415675
 2209406.2641691739321.0164978362209418.86781843 739420.21905534
2209463.37363492739770.5280660092209572.76170829739911.344966119
#Sta/Elev= 30
       0 1455.79    28.4 1462.08    52.5 1464.78    88.8 1463.89   112.4 1458.56
   141.3 1447.86   254.2  1411.7   270.3 1407.17   282.4 1406.27   298.5 1400.48
   322.7 1397.15   407.4 1394.84   423.5 1391.23   435.6 1390.87  441.96 1386.61
   447.7 1384.05   458.8 1383.69   556.6 1383.72   560.6 1384.69  562.28 1386.65
   568.7 1392.09   576.7  1396.3   661.4 1417.02   757.5 1432.48   790.4  1445.6
   826.7 1457.54   879.1 1468.37   943.5 1477.28  1019.5 1483.26    1083 1483.71
#Mann= 6 ,-1,0
       0      .1       0  265.31     .06       0  299.06      .1       0
  369.06    .025       0  441.96    .045       0  562.28      .1       0
Bank Sta=441.96,562.28
XS Rating Curve= 0 ,0
Exp/Cntr(USF)=0,0
Exp/Cntr=0.3,0.1

Type RM Length L Ch R = 1 ,17593   ,685.5,669.5,653.8
XS GIS Cut Line= 6
2208327.54681912739542.4171802832208500.16359988739633.797574951
2208958.63381154739876.5044386222209041.48994504739920.366883709
2209127.10788404739965.6919242872209495.33981124740176.466039084
#Sta/Elev= 30
       0 1501.33   104.8 1522.77   132.7 1523.19   158.4 1518.51   185.4 1508.66
   222.5 1486.55   258.7 1468.81   335.6 1424.13   351.7 1409.21   358.3 1407.25
   394.5  1405.7  419.95 1386.44   426.1 1383.99   434.6 1383.66   516.7 1383.73
   523.31386.421     547 1393.82   557.4 1395.31   664.2 1393.89   683.1 1392.33
   760.1 1403.69   792.7 1404.51   975.4 1422.14  1011.9  1421.9  1076.4 1438.99
  1099.5 1442.25  1185.5 1464.02  1215.8 1470.03  1294.9 1478.67    1329 1480.11
#Mann= 4 ,-1,0
       0      .1       0  419.95    .045       0   523.3     .07       0
  531.56      .1       0
Bank Sta=419.95,523.3
XS Rating Curve= 0 ,0
Exp/Cntr(USF)=0,0
Exp/Cntr=0.3,0.1

Type RM Length L Ch R = 1 ,16923   ,750,750,750.1
XS GIS Cut Line= 6
2208032.51954126740256.8420540092208127.38582134740283.116279677
2208220.74619892740308.973839507 2208636.3503546740424.080892757
 2208904.3849235740498.3163085882209162.58157589740559.480458951
#Sta/Elev= 30
       0 1498.38    71.5  1504.4      91 1503.87   103.4 1506.72   149.1 1502.65
   227.9 1471.54   244.5 1461.91   266.5 1459.06   269.4 1457.08   273.6  1448.5
   289.1 1411.24   294.3 1406.42   306.8 1404.75   323.4 1398.17   402.2  1401.7
  437.021386.687   447.9 1383.44   542.8 1383.47   547.4  1386.7   552.6 1391.33
   572.4 1395.09   659.6 1395.43   717.7 1401.33   858.8 1438.51   900.3  1442.8
   953.4 1453.06  1009.9 1457.27  1044.2 1464.35  1077.1 1467.19    1170 1467.74
#Mann= 6 ,-1,0
       0     .05       0      80      .1       0  386.56     .06       0
  437.02    .045       0   547.4     .07       0  591.56      .1       0
Bank Sta=437.02,547.4
XS Rating Curve= 0 ,0
Exp/Cntr(USF)=0,0
Exp/Cntr=0.3,0.1

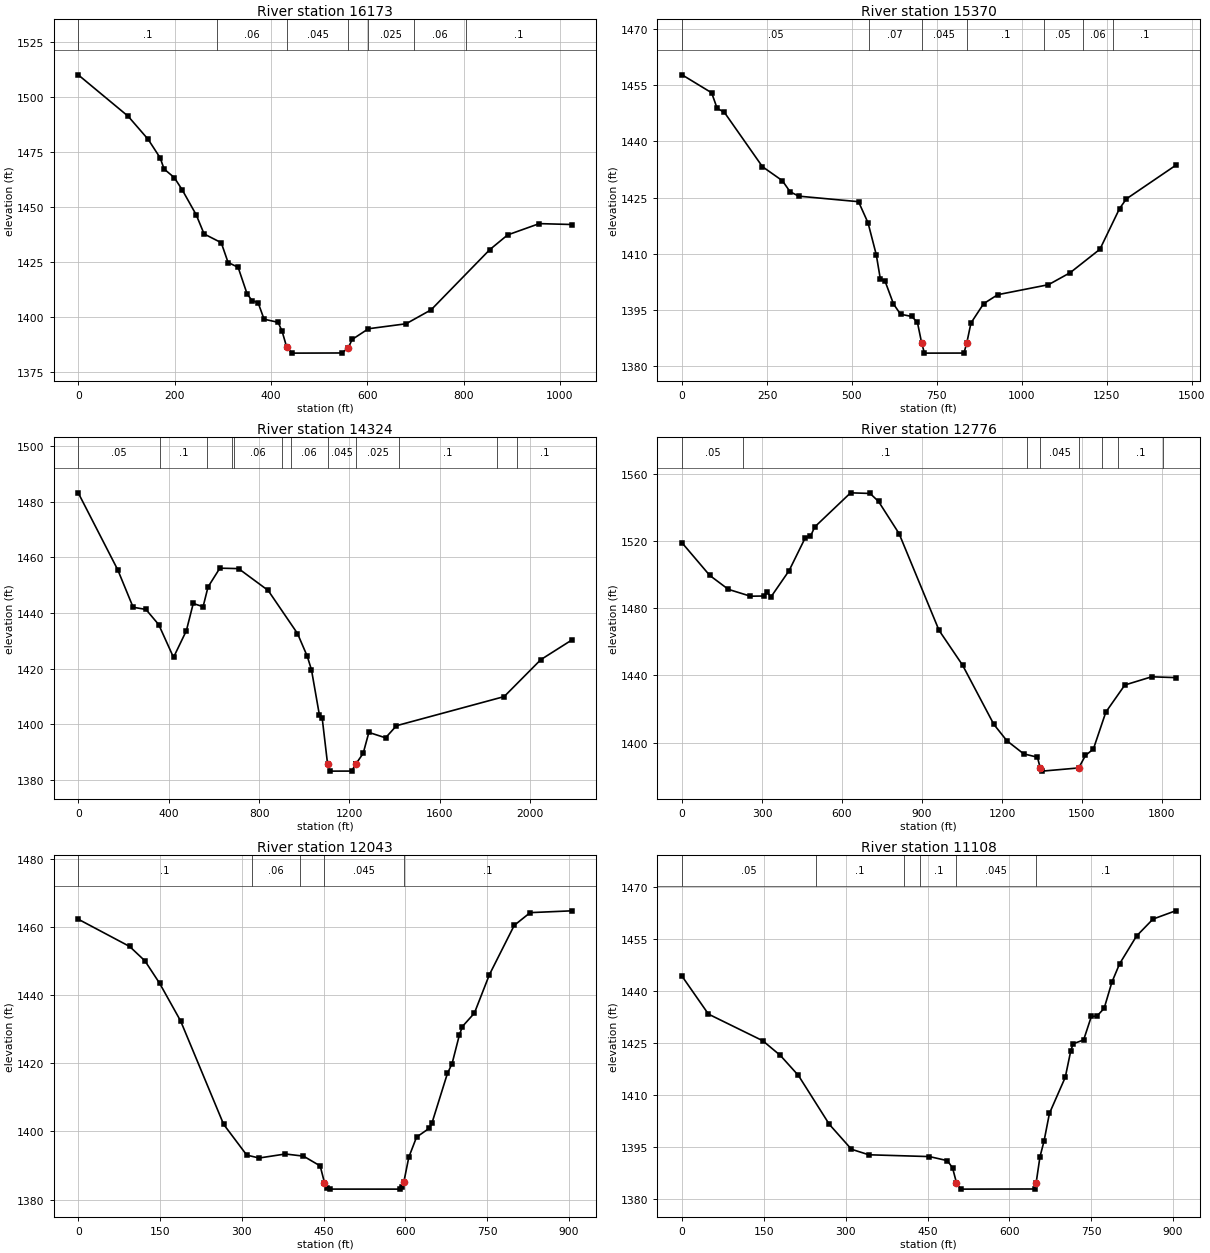
Type RM Length L Ch R = 1 ,16173   ,804.1,803.8,803.9
XS GIS Cut Line= 6
2207832.33326185740979.6319470112207927.19954193741005.906500757
2208195.23411085741080.1419165882208436.16407518741146.870785758
2208610.83859459741195.2489698382208821.81569546 741243.97651188
#Sta/Elev= 30
       0 1509.93   103.6 1491.11   145.1 1480.62     170 1472.23   178.3 1467.11
   199.4 1463.23   215.7 1457.72   244.9 1446.32   261.3 1437.61   296.9 1433.63
   311.1 1424.63   331.9 1422.46   350.5  1410.4   360.9 1407.27   373.4 1406.34
   385.8 1398.86   414.9 1397.44   423.2 1393.38  432.96    1386   443.9 1383.44
   547.7 1383.51  560.86 1385.99   568.5 1389.64   602.4 1394.52   680.5 1396.78
   732.5 1403.12   854.3 1430.48   891.3 1437.16     957  1442.3  1024.3  1441.9
#Mann= 7 ,-1,0
       0      .1       0  289.06     .06       0  432.96    .045       0
  560.86     .06       0  601.56    .025       0  696.56     .06       0
  804.06      .1       0
Bank Sta=432.96,560.86
XS Rating Curve= 0 ,0
Exp/Cntr(USF)=0,0
Exp/Cntr=0.3,0.1

Type RM Length L Ch R = 1 ,15370   ,1163.5,1045.7,909.3
XS GIS Cut Line= 6
2207502.94962442742235.6933138732207945.06559713741844.981268922
2208198.20879164741914.4417599232208354.91648348741957.441017756
2208445.32476722741982.2480547672208719.64246556741774.944627904
#Sta/Elev= 30
       0  1457.8      87    1453   103.1 1448.86   124.4 1447.78   236.5 1433.25
   295.2  1429.5   317.9 1426.55   343.3 1425.37   519.4 1423.89   547.4 1418.23
   571.6 1409.72   583.5 1403.29   597.4 1402.67   622.3 1396.56     643 1393.81
   676.2 1393.21   692.8 1391.61   705.2 1386.13   713.5 1383.41   829.7 1383.43
     838 1386.11   850.4 1391.47   887.7 1396.63   929.2 1399.03  1078.5  1401.7
  1142.4 1404.91    1230 1411.18  1287.8 1422.06  1307.9 1424.64  1452.6 1433.58
#Mann= 7 ,-1,0
       0     .05       0     550     .07       0   705.2    .045       0
     838      .1       0 1065.02     .05       0 1178.77     .06       0
 1268.77      .1       0
Bank Sta=705.2,838
XS Rating Curve= 0 ,0
Exp/Cntr(USF)=0,0
Exp/Cntr=0.3,0.1

Type RM Length L Ch R = 1 ,14324   ,1643.6,1548.3,1441.2
XS GIS Cut Line= 3
2208773.76007987 743888.017156192208351.96250343742914.409472076
2208705.39553424741849.724875111
#Sta/Elev= 30
       0 1483.14     175 1455.48   242.9 1442.05   299.5 1441.28   356.2 1435.81
   421.6 1424.05   478.3 1433.62   508.8 1443.41   552.4 1442.25   574.2 1449.33
   626.5 1456.09   709.3 1455.93   840.1  1448.1     970 1432.63  1013.2 1424.46
  1031.9 1419.58  1066.6  1403.5  1079.2  1402.3 1103.28 1385.63  1112.5 1383.22
  1209.9 1383.24  1226.7 1385.62  1226.7 1385.63  1260.4 1389.56  1285.7 1397.12
  1359.6 1395.18  1407.9 1399.53  1884.2 1409.98  2046.3 1423.24  2182.9 1430.27
#Mann= 12 ,-1,0
       0     .05       0     360      .1       0     570     .06       0
     680      .1       0     690     .06       0     900      .1       0
     940     .06       0 1103.28    .045       0  1226.7    .025       0
 1421.05      .1       0 1851.05     .06       0 1941.05      .1       0
Bank Sta=1103.28,1226.7
XS Rating Curve= 0 ,0
Exp/Cntr(USF)=0,0
Exp/Cntr=0.3,0.1

Type RM Length L Ch R = 1 ,12776   ,718.5,732.4,743.4
XS GIS Cut Line= 3
2210207.59446102742708.4446841672209757.50063833742103.112718242
2208865.41994951 741465.02181463
#Sta/Elev= 30
       0  1518.9   103.8 1499.53   173.5 1491.25   256.4 1487.17   307.8 1487.28
   318.1 1489.57   333.5 1486.75   401.3 1502.34   461.6 1521.79   481.7 1522.83
   497.5 1528.37   632.1 1548.69   705.2 1548.32   736.8 1543.58     814 1524.42
   963.9 1466.85    1052 1446.18  1169.5 1410.88  1218.3 1401.16  1281.3 1393.35
    1333 1391.34 1343.43 1384.95    1351 1383.06  1487.8 1384.96  1513.3 1392.42
  1542.8 1396.16  1589.6 1418.18  1660.9 1434.32  1761.5  1439.2  1851.1 1438.72
#Mann= 8 ,-1,0
       0     .05       0     230      .1       0 1294.33    .025       0
 1343.43    .045       0  1487.8     .08       0 1574.33     .06       0
 1634.33      .1       0 1804.33     .08       0
Bank Sta=1343.43,1487.8
XS Rating Curve= 0 ,0
Exp/Cntr(USF)=0,0
Exp/Cntr=0.3,0.1

Type RM Length L Ch R = 1 ,12043   ,911,935,959
XS GIS Cut Line= 6
2210012.76934049741477.4094023422209738.71181774741219.161559255
 2209611.3488835741099.1463793382209493.08370008740987.703360767
2209424.85352157740923.409526096 2209354.3490694740856.972323016
#Sta/Elev= 30
       0 1462.26    94.3 1454.25   122.3 1450.03   149.2 1443.46   187.7 1432.41
   266.6 1402.07     309 1393.04   331.7 1392.19   379.8 1393.37     413 1392.74
   443.6 1389.87   451.5 1384.95   456.2 1383.34   461.1 1383.07   589.2 1383.06
   594.4 1383.64  596.831385.024   606.1 1392.42   620.3 1398.32   643.9 1400.95
   648.6 1402.48   676.9 1417.01   685.4 1419.87   698.8 1428.27   704.3 1430.76
   726.3 1434.69   753.8 1445.96   799.4 1460.45   828.6 1464.18   904.7 1464.71
#Mann= 5 ,-1,0
       0      .1       0  319.06     .06       0  406.56      .1       0
   451.5    .045       0  596.83      .1       0
Bank Sta=451.5,596.83
XS Rating Curve= 0 ,0
Exp/Cntr(USF)=0,0
Exp/Cntr=0.3,0.1

Type RM Length L Ch R = 1 ,11108   ,923.4,934.9,947.2
XS GIS Cut Line= 6
2210598.85566416740950.152411684  2210399.867217740630.460465774
2210267.75888541740418.216795772  2210221.521117740343.931511268
2210171.98020558740264.3401350232210120.78837883740182.095548853
#Sta/Elev= 30
       0 1444.23    48.3 1433.34   147.9 1425.67   180.2 1421.43   213.2 1415.69
     270 1401.58   310.5 1394.42   342.4 1392.83   453.5 1392.31   486.4 1391.14
   495.9 1389.05  502.92 1384.84   510.9 1382.94   646.6 1382.98   649.2 1384.83
   656.1 1392.22   663.6 1396.78   673.5 1404.76   702.5 1415.14   712.6 1422.78
     717 1424.79   736.2 1425.91   750.3 1432.66   760.6 1432.77   773.8    1435
     788 1442.54   802.1 1447.82   833.2 1455.83   863.4 1460.71   904.7 1463.08
#Mann= 6 ,-1,0
       0     .05       0  245.31      .1       0  406.56     .05       0
  436.56      .1       0  502.92    .045       0   649.2      .1       0
Bank Sta=502.92,649.2
XS Rating Curve= 0 ,0
Exp/Cntr(USF)=0,0
Exp/Cntr=0.3,0.1