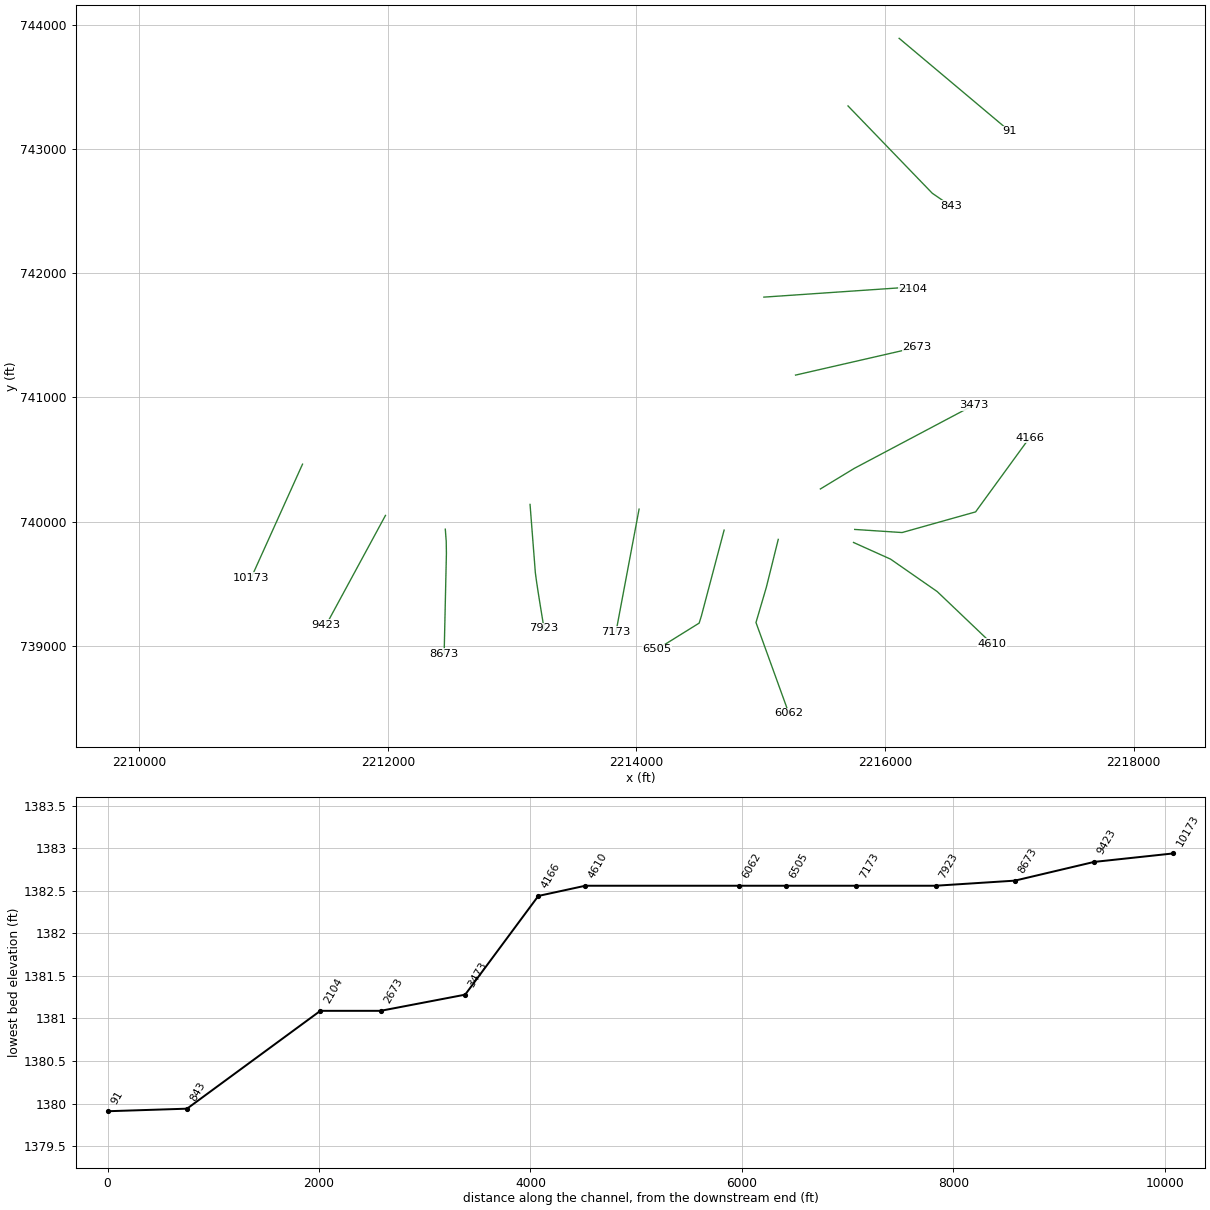
HEC-RAS study BUCKHANR_L.prj: BUCKHANR_L

--- BUCKHANR_L.g01 (geometry) --- (continued)

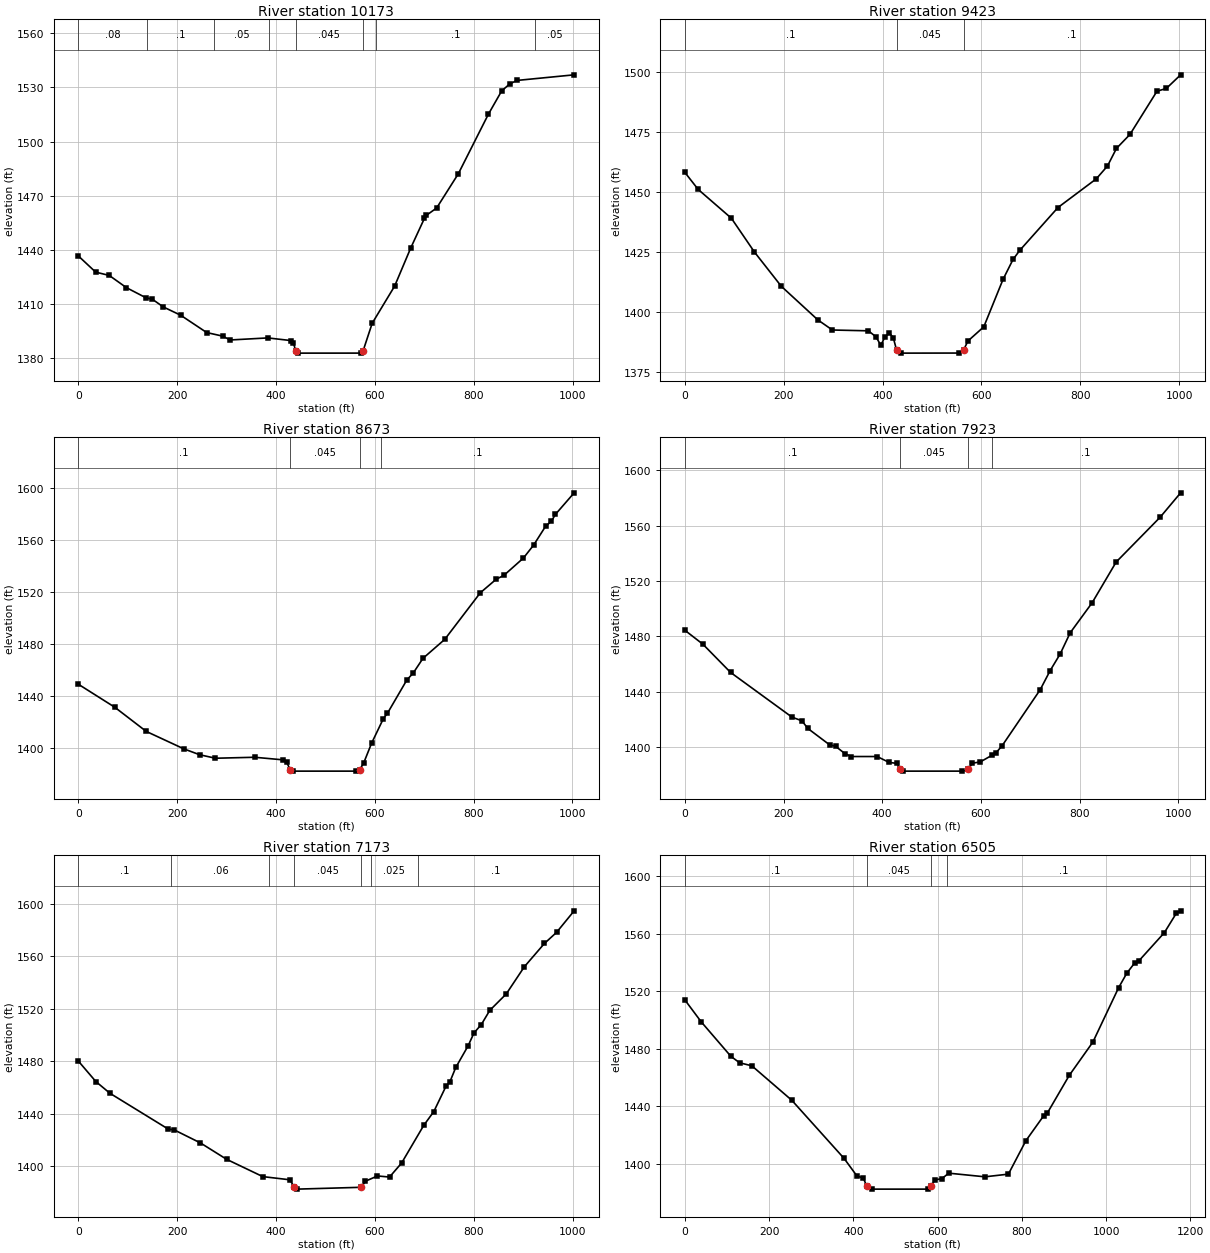
Type RM Length L Ch R = 1 ,10173   ,754.8,750,741.9
XS GIS Cut Line= 6
2211313.89782101740461.8856071682211273.40610409740372.161705256
2211159.00180534 740118.655978682211128.15147334740050.294894919
2211087.01736926739959.1467832622210901.27069351739547.556070998
#Sta/Elev= 30
       0 1436.73    35.1 1427.77    62.5 1425.95    97.3 1419.18   136.8 1413.58
     150 1412.72   171.9  1408.5     207 1403.93   259.7 1394.33   292.1 1392.34
   307.2 1390.22   383.4 1391.36   430.8 1389.87   435.2  1388.6   439.6 1384.23
     444 1382.94   571.3 1382.95  576.241384.317   594.5 1399.47   639.9 1420.03
   672.2 1440.97   700.3 1457.62   704.3 1459.24   724.9 1463.27   768.8 1482.24
   829.7 1515.24   856.5 1528.09   872.7 1531.92   887.2 1533.87  1003.1 1536.98
#Mann= 8 ,-1,0
       0     .08       0  138.44      .1       0  275.31     .05       0
  386.56      .1       0   439.6    .045       0  576.24    .025       0
  601.56      .1       0  924.69     .05       0
Bank Sta=439.6,576.24
XS Rating Curve= 0 ,0
Exp/Cntr(USF)=0,0
Exp/Cntr=0.3,0.1

Type RM Length L Ch R = 1 ,9423    ,704.8,750,789.3
XS GIS Cut Line= 6
2211981.02411142740049.0918133412211888.01248643739877.348062336
2211843.36723451739794.9112193442211765.98156251739652.020757094
2211682.64347459739498.1385189292211503.31706159739167.016805843
#Sta/Elev= 30
       0 1458.31    27.1 1451.16    94.2 1439.15   140.9 1425.03   195.3 1410.73
   269.1 1396.72   298.6 1392.49   371.4 1392.15   386.6 1389.68   396.6 1386.13
   404.8 1389.57   413.9 1391.19   421.8 1389.28   428.4 1384.14   436.6 1382.84
   554.9 1382.87     564 1384.17   572.9 1387.92   604.9 1393.82   643.8 1413.61
     664 1421.93   677.7 1425.74     755 1443.62   832.4 1455.57   855.1 1460.94
   873.3 1468.29   900.6 1474.12   955.2 1492.14   974.3 1493.33  1003.1    1499
#Mann= 3 ,-1,0
       0      .1       0   428.4    .045       0     564      .1       0
Bank Sta=428.4,564
XS Rating Curve= 0 ,0
Exp/Cntr(USF)=0,0
Exp/Cntr=0.3,0.1

Type RM Length L Ch R = 1 ,8673    ,737.4,750,758.8
XS GIS Cut Line= 6
2212462.40536651739938.4345543382212469.77313392739839.806798846
2212471.23376092739742.8749060932212465.48574093739486.689394832
2212455.32073501739033.6781617552212453.11273417738935.265628919
#Sta/Elev= 30
       0  1449.3    73.5 1431.71   137.5 1413.09   213.5 1399.72   245.6 1395.19
   277.6 1392.51     357 1393.26   413.6  1391.3   421.6 1389.67  428.671383.775
   433.6 1382.62   561.6 1382.62   569.6 1383.73   577.6 1388.82   593.6 1404.01
   617.6 1422.99   625.6 1426.91   665.1 1452.62   677.7 1457.76   697.7 1469.18
   741.7 1483.69   813.7 1519.46   845.7  1529.8   861.7 1532.89     901 1546.12
   921.7 1556.08   945.7 1570.38   957.7 1574.42   965.7 1579.59  1003.7 1596.16
#Mann= 4 ,-1,0
       0      .1       0  428.67    .045       0   569.6    .025       0
   612.1      .1       0
Bank Sta=428.67,569.6
XS Rating Curve= 0 ,0
Exp/Cntr(USF)=0,0
Exp/Cntr=0.3,0.1

Type RM Length L Ch R = 1 ,7923    ,771.9,750,722.9
XS GIS Cut Line= 6
2213144.07985617740137.7464916712213186.71330109739587.834205672
2213196.79070875739513.3904569152213210.00229651739426.652113333
2213224.78113835 739333.766472342213256.29616718739140.311150596
#Sta/Elev= 30
       0 1484.38    36.7 1474.26    92.8 1453.86   217.2 1421.56   237.3 1418.92
   249.3 1413.39   293.4 1401.55   305.5 1400.52   324.5 1395.16   337.6 1393.11
   389.7 1393.11   413.8 1388.88   429.9 1388.14  436.881383.862   441.9 1382.56
   562.3 1382.56   574.4 1383.86   582.5  1388.3   598.6  1389.2   622.8 1394.13
   630.9 1395.98   643.1 1401.03     720 1441.39   740.2 1455.22   760.5 1467.24
   780.7 1482.48   825.3 1504.26   873.9 1533.65   963.1 1566.06  1004.5 1583.66
#Mann= 4 ,-1,0
       0      .1       0  436.88    .045       0   574.4    .025       0
  621.56      .1       0
Bank Sta=436.88,574.4
XS Rating Curve= 0 ,0
Exp/Cntr(USF)=0,0
Exp/Cntr=0.3,0.1

Type RM Length L Ch R = 1 ,7173    ,674.6,668.6,661.8
XS GIS Cut Line= 6
2214021.15421751740099.9778664262213985.09621875739908.022541672
 2213937.7885706739656.1772448422213919.32666525739557.896273419
2213872.01901709739306.0509765892213835.96101834739114.095651835
#Sta/Elev= 30
       0 1480.24    35.4 1464.62    63.9 1455.67   181.9 1428.34   194.1 1427.71
     247  1417.8     300  1405.3   373.2  1392.1   428.1 1389.68  437.02 1383.94
   442.4 1382.56   572.6 1383.96   580.8 1388.61   605.2  1392.6   629.6 1391.78
     654 1402.45   698.8 1431.19   719.2 1441.74   743.6 1460.86   751.7  1464.4
   763.6 1475.35   788.4 1491.73   800.6 1501.77   815.3 1508.08   832.4 1518.88
   865.7  1531.4   902.3 1552.13     943 1569.93   967.4 1578.33  1003.1  1594.8
#Mann= 7 ,-1,0
       0      .1       0  188.44     .06       0  386.56      .1       0
  437.02    .045       0   572.6      .1       0  591.56    .025       0
  686.56      .1       0
Bank Sta=437.02,572.6
XS Rating Curve= 0 ,0
Exp/Cntr(USF)=0,0
Exp/Cntr=0.3,0.1

Type RM Length L Ch R = 1 ,6505    ,445.1,442.4,440.4
XS GIS Cut Line= 6
2214705.12812245739930.9839040232214679.95428829739835.822348926
2214564.08509744739397.7622014322214522.53235903 739240.66507468
2214504.44016244739182.3764148972214163.39055361 738970.03218803
#Sta/Elev= 30
       0 1514.14    39.1 1498.78   109.4 1474.86   130.1 1470.37   159.1 1468.28
     254 1444.31   378.1 1403.89     408 1391.92   423.9 1390.06   432.2 1384.51
     444 1382.56     577 1382.56   584.7 1384.64   593.5 1388.93   610.1 1389.86
   626.6 1393.65   712.3 1391.12     768 1392.97   809.6 1416.24   851.7 1433.51
   860.4  1435.4   912.6 1461.67   968.6  1484.8  1029.8 1522.67  1049.1 1532.65
  1067.5 1539.68    1077 1540.99  1138.2 1560.82  1166.5 1574.27  1176.8 1575.99
#Mann= 4 ,-1,0
       0      .1       0   432.2    .045       0   584.7    .025       0
  621.56      .1       0
Bank Sta=432.2,584.7
XS Rating Curve= 0 ,0
Exp/Cntr(USF)=0,0
Exp/Cntr=0.3,0.1

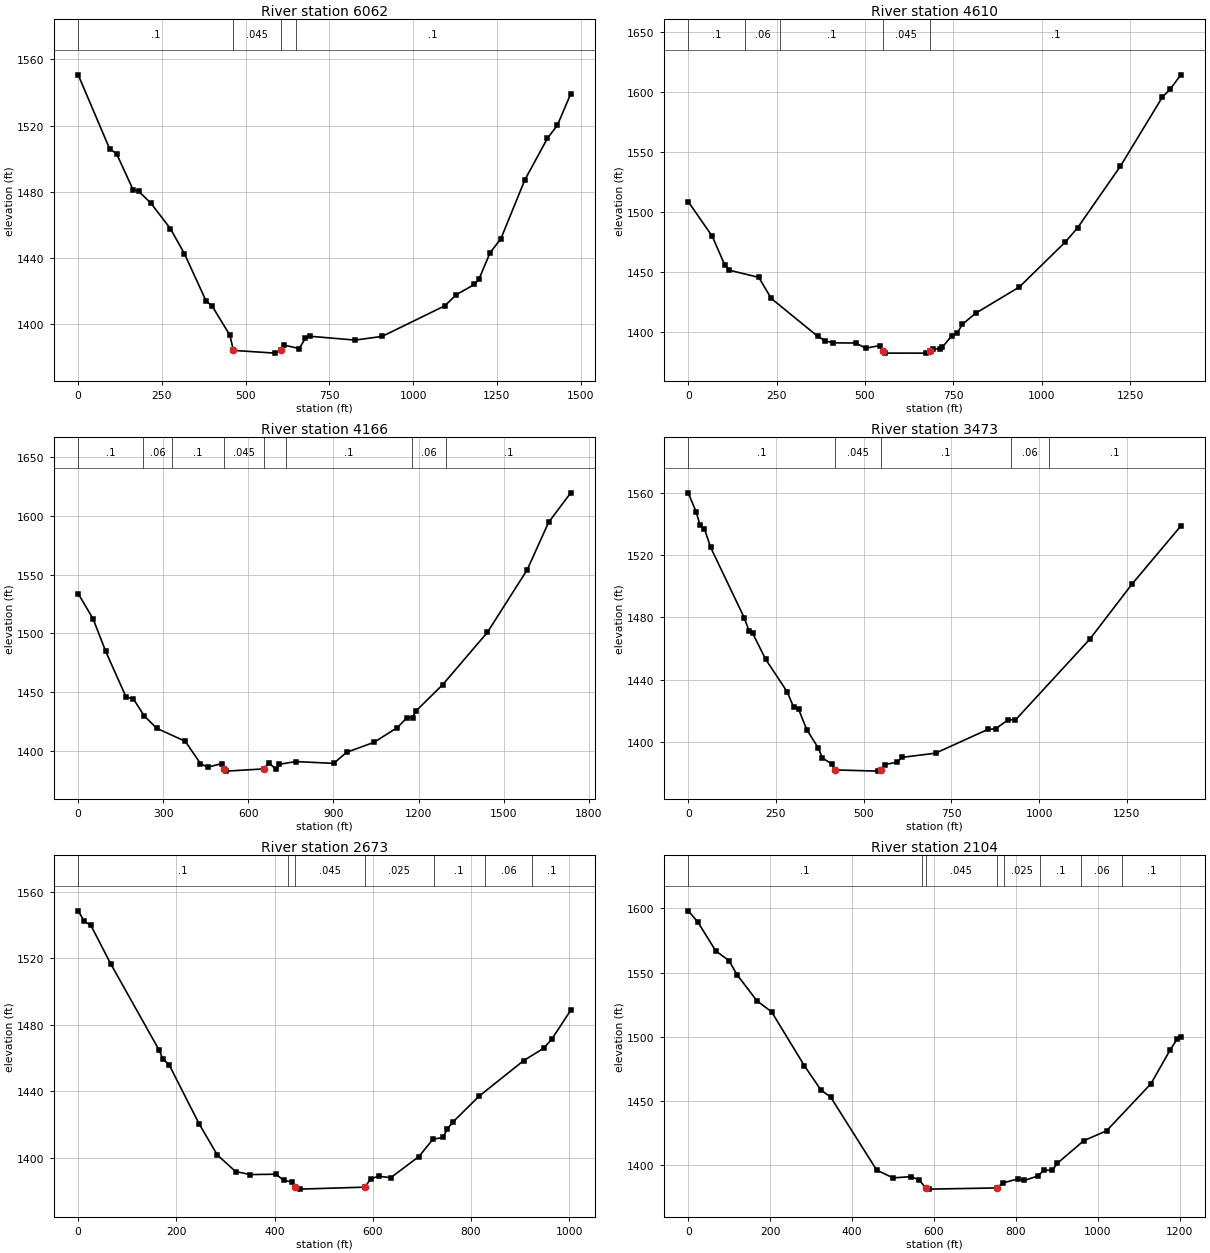
Type RM Length L Ch R = 1 ,6062    ,1340,1452.1,1561
XS GIS Cut Line= 4
2215140.67809116739856.2494590352215044.38031667739468.878877729
2214961.50701703739187.1774221112215226.07994994738455.625068873
#Sta/Elev= 30
       0  1550.6    93.8 1505.99   114.5 1503.03   163.9 1481.25   180.4  1480.4
   217.5    1473   275.2 1457.79   317.1 1442.67   382.4 1413.83   399.2 1411.23
   453.1 1393.33   463.4 1384.22   586.5 1382.56   605.3 1384.21   615.7 1387.39
     660  1385.3   678.2 1391.49   690.7 1392.77   826.8 1390.43   907.6 1392.66
  1094.8 1411.15  1128.8  1417.8  1182.9 1424.01  1196.3 1427.05  1229.9 1443.23
  1261.9 1451.54  1333.7 1487.19    1401 1512.24  1430.8 1520.15  1470.7 1539.15
#Mann= 4 ,-1,0
       0      .1       0   463.4    .045       0   605.3    .025       0
  649.16      .1       0
Bank Sta=463.4,605.3
XS Rating Curve= 0 ,0
Exp/Cntr(USF)=0,0
Exp/Cntr=0.3,0.1

Type RM Length L Ch R = 1 ,4610    ,372.6,444.7,527.6
XS GIS Cut Line= 4
2215746.07817674739831.4200145472216043.83906419739697.416993867
2216419.36427625739436.1782497012216860.11597595739015.598656582
#Sta/Elev= 30
       0 1508.88    68.1 1479.93   103.2 1456.19   116.3 1451.69   199.7  1445.7
   234.8 1428.18   365.9 1396.66   387.3 1392.81   410.3 1391.14   473.5 1390.98
   502.1 1386.72   541.3 1388.79   549.91384.073     556 1382.57   672.9 1382.56
  683.98 1384.02   691.9 1386.21   711.9 1386.04   719.2 1387.64     746 1397.23
   761.2 1399.43   775.2 1406.53   812.7 1415.77   936.6 1437.68  1067.1 1475.36
  1101.2 1486.98  1222.4 1538.39  1341.2 1596.05  1363.8 1602.77  1393.2 1614.59
#Mann= 5 ,-1,0
       0      .1       0     160     .06       0     260      .1       0
   549.9    .045       0  683.98      .1       0
Bank Sta=549.9,683.98
XS Rating Curve= 0 ,0
Exp/Cntr(USF)=0,0
Exp/Cntr=0.3,0.1

Type RM Length L Ch R = 1 ,4166    ,679.2,692.1,720.1
XS GIS Cut Line= 4
2215755.59727826739936.3424760032216136.62644607739911.332839505
2216728.03079147740077.5733644572217163.49269754740676.333485301
#Sta/Elev= 30
       0 1533.79    52.7 1512.23    96.8 1484.69   168.9 1445.62   194.6 1444.07
   233.1 1429.45   277.2 1418.94   377.4 1407.89   431.2 1388.91   456.2 1385.79
     506 1388.85   514.3 1384.31   522.7 1382.44  654.44 1384.34   672.2 1389.47
   697.2 1383.98   709.6 1388.29   767.8 1390.59   900.8 1389.05   946.5 1398.49
  1041.8 1406.89  1124.9 1419.51  1159.2 1428.01  1178.7 1428.08  1190.7 1433.66
  1285.2 1456.18  1442.7 1500.77    1583 1554.13  1658.4 1594.55  1736.5 1619.71
#Mann= 8 ,-1,0
       0      .1       0     230     .06       0     330      .1       0
   514.3    .045       0  654.44    .025       0  731.85      .1       0
 1176.17     .06       0 1296.17      .1       0
Bank Sta=514.3,654.44
XS Rating Curve= 0 ,0
Exp/Cntr(USF)=0,0
Exp/Cntr=0.3,0.1

Type RM Length L Ch R = 1 ,3473    ,829,800.1,786.1
XS GIS Cut Line= 3
2215479.64067496740262.1614542752215752.28126221740427.903199601
2216710.34754874740935.713506024
#Sta/Elev= 30
       0 1559.84      23 1547.41    33.4 1539.32    46.3 1536.68    63.7 1524.95
   159.8 1479.63   173.8  1470.9   183.2 1469.91   220.6 1453.06   282.1 1432.14
   300.2  1422.4   314.3 1421.09   337.7 1407.94   370.2 1396.27   382.3 1389.77
   409.5 1385.78   418.5 1382.05   540.8 1381.28  549.82 1382.07   560.9  1385.5
   595.1 1387.03   608.7  1390.1   704.6 1392.79   853.1 1407.99   875.8 1408.46
     912 1414.28   932.4 1414.11  1144.2 1465.96  1265.1 1501.48  1403.4 1538.51
#Mann= 5 ,-1,0
       0      .1       0   418.5    .045       0  549.82      .1       0
  919.07     .06       0 1029.07      .1       0
Bank Sta=418.5,549.82
XS Rating Curve= 0 ,0
Exp/Cntr(USF)=0,0
Exp/Cntr=0.3,0.1

Type RM Length L Ch R = 1 ,2673    ,583.3,569.5,551.5
XS GIS Cut Line= 6
2215279.80786817741178.8005119262215470.17953467741222.454624087
2215561.55763276741243.4083223342215719.94675167741279.728459671
2216067.18424617741359.3536285012216257.55591267741403.007412583
#Sta/Elev= 30
       0 1548.49    12.7 1542.08    25.7 1539.86      66 1516.75   164.5 1464.89
   172.7 1459.22     185    1456   246.6 1420.19   283.5  1401.6   320.5 1391.69
   350.7 1389.84   402.6 1390.06     419 1386.32   435.4 1385.42  441.571382.308
   451.6 1381.09  584.19 1382.29   595.4 1387.24   611.8 1388.86   636.5 1387.97
   693.9 1400.69   722.6 1411.14   743.2 1412.16   751.4 1417.18   763.4 1421.55
     817 1437.13   907.3 1458.41   948.4 1465.91   964.8 1471.44  1003.1 1488.71
#Mann= 7 ,-1,0
       0      .1       0  426.56     .06       0  441.57    .045       0
  584.19    .025       0  724.06      .1       0  827.81     .06       0
  924.69      .1       0
Bank Sta=441.57,584.19
XS Rating Curve= 0 ,0
Exp/Cntr(USF)=0,0
Exp/Cntr=0.3,0.1

Type RM Length L Ch R = 1 ,2104    ,1335.6,1261.3,1158.4
XS GIS Cut Line= 3
2215025.05403326741806.478753962 2216108.9334327741880.745972075
2216225.00018985741872.370854869
#Sta/Elev= 30
       0 1598.15    23.2 1589.53    67.3 1566.89    99.4 1559.35   119.4 1548.28
   167.5 1528.08   203.6 1519.37   283.8 1477.29   323.9 1458.48   347.9 1452.83
   460.2 1395.95   500.3 1389.85   544.4 1390.84   564.4 1388.16   579.6 1382.07
   588.5 1381.09   752.9 1382.02   768.9 1385.92     805 1389.09     821 1387.85
   853.1 1391.29   869.2 1395.82   889.2 1395.84   901.2  1401.2     966 1418.89
  1021.5 1426.56  1129.8 1463.24  1176.8 1489.61  1193.9 1498.16  1202.8 1500.06
#Mann= 8 ,-1,0
       0      .1       0     570     .06       0   579.6    .045       0
   752.9     .06       0     770    .025       0     860      .1       0
     960     .06       0    1060      .1       0
Bank Sta=579.6,752.9
XS Rating Curve= 0 ,0
Exp/Cntr(USF)=0,0
Exp/Cntr=0.3,0.1

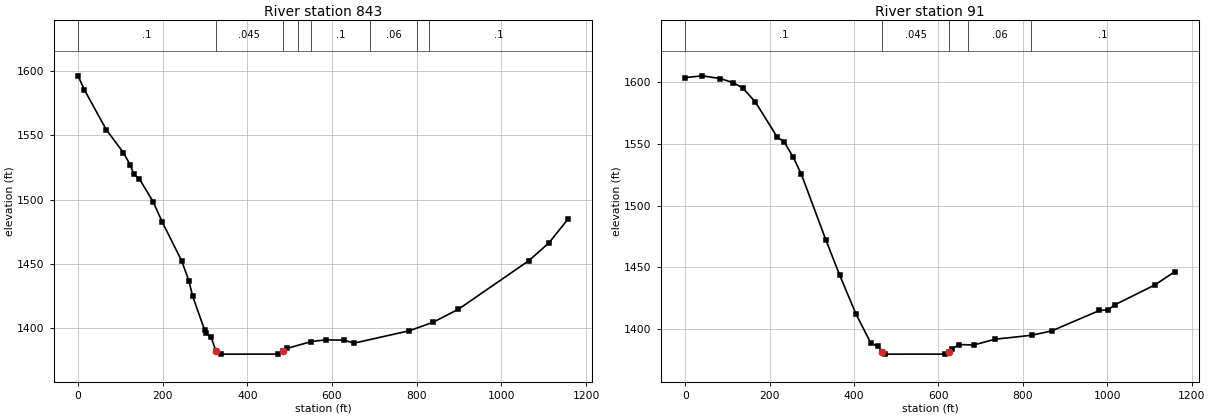
Type RM Length L Ch R = 1 ,843     ,739.2,752,754.9
XS GIS Cut Line= 3
2215701.81312642743345.6016342372216380.09847847742642.146479297
2216528.54495134742540.896508172
#Sta/Elev= 30
       0  1596.4    14.9 1585.63      67 1554.36   107.1 1536.68   123.6 1526.96
   132.1 1519.79   145.1 1516.12   177.4 1498.47   199.3 1482.46   245.3 1452.16
   262.2 1436.59   270.7 1425.11     299 1398.74   303.1    1396   314.6 1393.03
   326.1  1382.1   337.6 1379.94   472.9 1379.95  483.27 1382.12   493.2 1384.33
   550.8 1389.69   585.4 1391.05   628.5 1390.79   652.6 1388.52   782.7 1398.12
   839.3 1404.79   898.7 1414.87  1065.2 1452.67  1112.9  1466.6  1156.9 1484.76
#Mann= 8 ,-1,0
       0      .1       0   326.1    .045       0  483.27      .1       0
     520    .025       0     550      .1       0     690     .06       0
     800     .07       0     830      .1       0
Bank Sta=326.1,483.27
XS Rating Curve= 0 ,0
Exp/Cntr(USF)=0,0
Exp/Cntr=0.3,0.1

Type RM Length L Ch R = 1 ,91      ,,,
XS GIS Cut Line= 2
2216113.15718443743889.7565981762217001.16592233743142.888321929
#Sta/Elev= 30
       0 1603.36    40.5 1604.78    82.3 1602.62   113.3 1599.29     136 1594.99
     166 1583.72   218.3 1555.09   233.9 1551.69   255.7 1539.16   275.1 1525.29
   333.2  1472.2   365.9 1443.74   404.8 1412.13   439.7 1388.85   456.8 1386.14
     467 1381.47   474.3 1379.91   616.1 1379.92  624.76 1381.42   631.1 1384.23
   649.8 1387.65   683.4 1387.27   734.2 1391.96   821.2 1395.17   868.4 1398.69
   981.3 1415.17  1001.9 1415.66  1017.9 1419.76  1113.3 1435.93  1160.3 1446.64
#Mann= 5 ,-1,0
       0      .1       0     467    .045       0  624.76    .025       0
     670     .06       0     820      .1       0
Bank Sta=467,624.76
XS Rating Curve= 0 ,0
Exp/Cntr(USF)=0,0
Exp/Cntr=0.3,0.1
LCMann Table=0

Chan Stop Cuts=-1
Use User Specified Reach Order=0
Composite Channel Slope=5